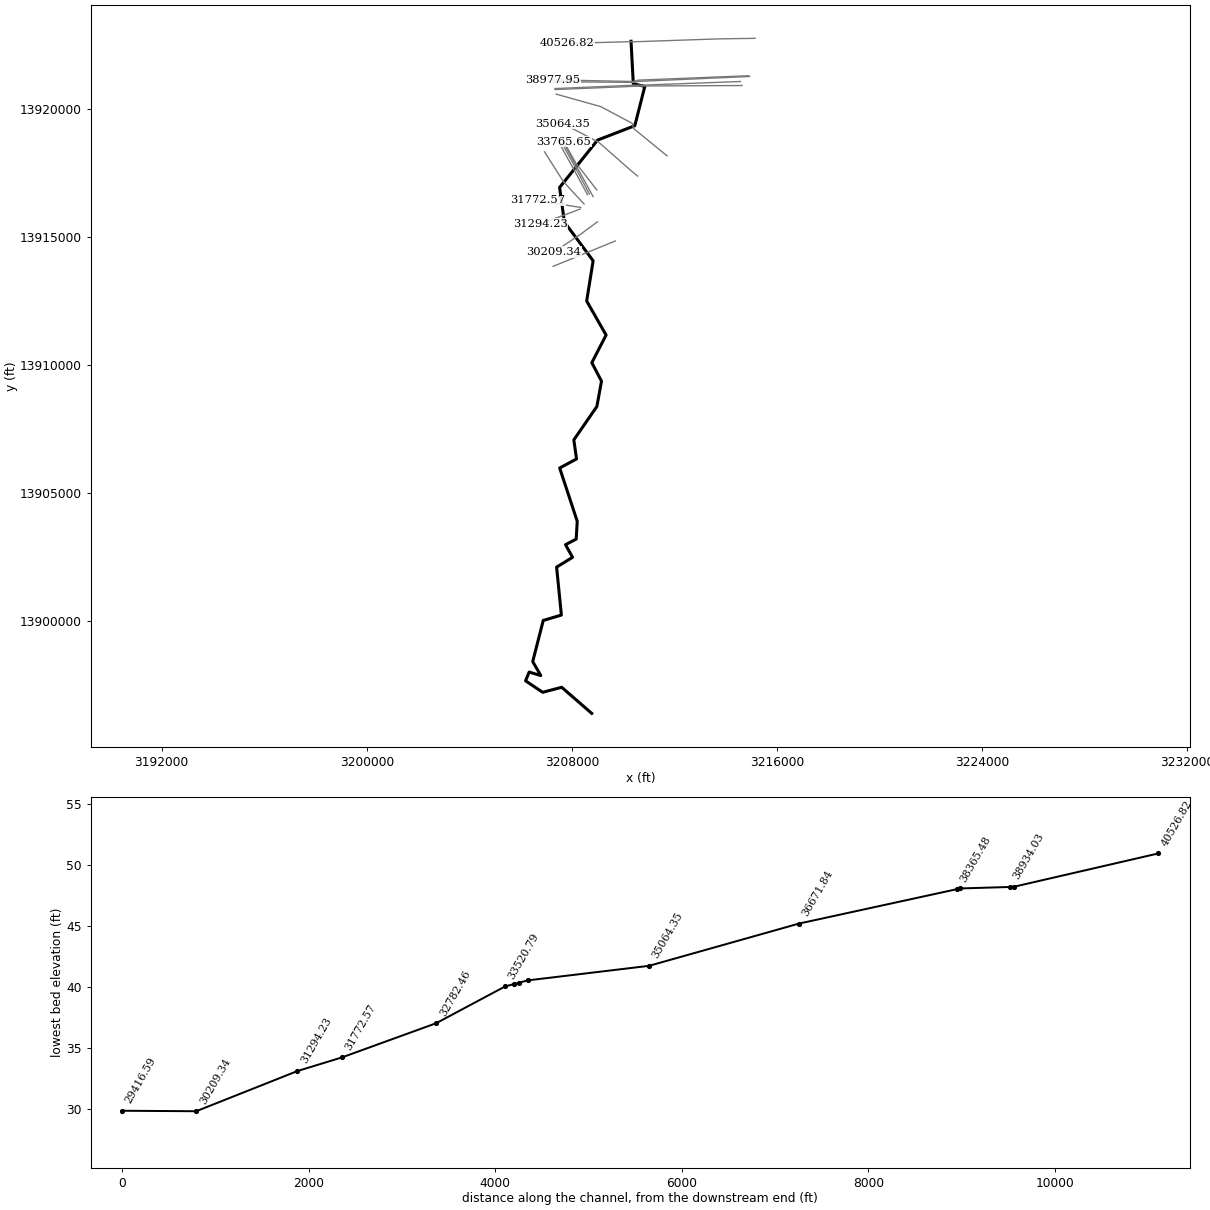
--- R102-00-00.prj (project) ---

Proj Title=R102-00-00
Current Plan=p03
Default Exp/Contr=.3,.1
English Units
Geom File=g03
Flow File=f02
Flow File=f04
Plan File=p01
Plan File=p03
Y Axis Title=Elevation
X Axis Title(PF)=Main Channel Distance
X Axis Title(XS)=Station
BEGIN DESCRIPTION:
Jackson Bayou Watershed
Gum Gully
HCFCD unit R 102-00-00
Flood Hazard Model
10, 2, 1, 0.2% Event
Filename R1020000.prj
Prepared by:  FTN Associates Ltd.   DATE: May 2003
Reviewed by:_____________    DATE:_______________
STATUS (FINAL RAS)
Normal depth calculated between RS 8506.231 and RS 1796.011 with inverts 6.04 and 1.54 respectively. Distance between cross sections is 6710.22. This results in a slope of 0.00067
Manning's n values adapted from existing Hec-2 model
END DESCRIPTION:
DSS File=dss
DSS Export Rating Curves= 0
DSS Export Rating Curve Sorted= 0
DSS Export Volume Flow Curves= 0
DXF OffsetX= 0
DXF OffsetY= 0
DXF ScaleX= 1
DXF ScaleY= 10

--- R102-00-00.p03 (plan) ---

Plan Title=Floodway
Version=Version 3.0.1  Mar 2001
Short Identifier=Floodway0607
Geom File=g03
Flow File=f04
Subcritical Flow
K Sum by GR= 0
Std Step Tol= 0.01
Critical Tol= 0.01
Num of Std Step Trials= 20
Max Error Tol= 0.3
Flow Tol Ratio= 0.001
Split Flow NTrial= 30
Split Flow Tol= 0.02
Split Flow Ratio= 0.02
Log Output Level= 0
Friction Slope Method= 1
Unsteady Friction Slope Method= 2
Parabolic Critical Depth
Global Vel Dist= 0 , 0 , 0
Global Log Level= 0
CheckData=True
Encroach Param=-1 ,0,0, 2
Encroach River=R102-00-00
Encroach Reach=Gum Gully
Encroach Node=40526.82
       1    4150    5400
Encroach Node=38977.95
       1    4250    4850
Encroach Node=38934.03
       1    4250    4850
Encroach Node=38667.31
       1    4200    4900
Encroach Node=38400.59
       1    4100    5000
Encroach Node=38365.48
       1    3350    4250
Encroach Node=36671.84
       1 1771.22    2700
Encroach Node=35064.35
       1    1825    2600
Encroach Node=33765.65
       1    1140    1295
Encroach Node=33671.14
       1 1139.45  1290.4
Encroach Node=33643.14
       1 1139.45  1290.4
Encroach Node=33615.15
       1 1139.45  1290.4
Encroach Node=33520.79
       1 1041.16 1144.63
Encroach Node=32782.46
       1    1160 1323.96
Encroach Node=31772.57
       1  757.21  841.67
Encroach Node=31294.23
       1  671.45  778.82
Encroach Node=30209.34
       1  784.75  961.61
Encroach Node=29416.59
       1 1139.71 1240.31
Encroach Node=28526.83
       1 1436.96 1610.69
Encroach Node=28433.63
       1 1406.16 1629.51
Encroach Node=28371.02
       1 1406.16 1640.53
Encroach Node=28308.41
       1 1421.97 1640.53
Encroach Node=28207.62
       1 1497.42 1671.65
Encroach Node=26857.31
       1   834.2  934.84
Encroach Node=25334.36
       1  803.34  910.58
Encroach Node=24048.65
       1 2852.07 2967.31
Encroach Node=22198.61
       1  707.41  817.57
Encroach Node=21180.61
       1     861     985
Encroach Node=19885.91
       1  957.87    1154
Encroach Node=18881.20
       1  925.62    1115
Encroach Node=18039.75
       1     211     450
Encroach Node=16977.06
       1     649    1000
Encroach Node=16298.86
       1     600     985
Encroach Node=15149.71
       1    1158    1435
Encroach Node=14695.24
       1     925    1295
Encroach Node=14126.29
       1     825    1250
Encroach Node=12669.70
       1     900    1125
Encroach Node=11170.67
       1     665     933
Encroach Node=10399.98
       1     780     925
Encroach Node=9375.575
       1     937    1175
Encroach Node=8506.231
       1     700    1079
Encroach Node=7392.173
       1     850    1275
Encroach Node=6887.697
       1    1000 1186.48
Encroach Node=6784.822
       1     946    1145
Encroach Node=6761.167
       1  946.35    1145
Encroach Node=6737.510
       1     948    1145
Encroach Node=6632.963
       1     797    1050
Encroach Node=6259.743
       1    1010    1460
Encroach Node=5762.725
       1    2000    2250
Encroach Node=4911.257
       1 1904.28    2330
Encroach Node=3115.645
       1    1600 2382.61
Encroach Node=1796.011
       1    1250    1800
Encroach Node=202.802
       1     343     917
Encroach Reach=R102-00-00_0002
Encroach Node=40526.82
       1    4150    5400
Encroach Node=38977.95
       1    4250    4850
Encroach Node=38934.03
       1    4250    4850
Encroach Node=38667.31
       1    4200    4900
Encroach Node=38400.59
       1    4100    5000
Encroach Node=38365.48
       1    3350    4250
Encroach Node=36671.84
       1 1771.22    2700
Encroach Node=35064.35
       1    1825    2600
Encroach Node=33765.65
       1    1140    1295
Encroach Node=33671.14
       1 1139.45  1290.4
Encroach Node=33643.14
       1 1139.45  1290.4
Encroach Node=33615.15
       1 1139.45  1290.4
Encroach Node=33520.79
       1 1041.16 1144.63
Encroach Node=32782.46
       1    1160 1323.96
Encroach Node=31772.57
       1  757.21  841.67
Encroach Node=31294.23
       1  671.45  778.82
Encroach Node=30209.34
       1  784.75  961.61
Encroach Node=29416.59
       1 1139.71 1240.31
Encroach Node=28526.83
       1 1436.96 1610.69
Encroach Node=28433.63
       1 1406.16 1629.51
Encroach Node=28371.02
       1 1406.16 1640.53
Encroach Node=28308.41
       1 1421.97 1640.53
Encroach Node=28207.62
       1 1497.42 1671.65
Encroach Node=26857.31
       1   834.2  934.84
Encroach Node=25334.36
       1  803.34  910.58
Encroach Node=24048.65
       1 2852.07 2967.31
Encroach Node=22198.61
       1  707.41  817.57
Encroach Node=21180.61
       1     861     985
Encroach Node=19885.91
       1  957.87    1154
Encroach Node=18881.20
       1  925.62    1115
Encroach Node=18039.75
       1     211     450
Encroach Node=16977.06
       1     649    1000
Encroach Node=16298.86
       1     600     985
Encroach Node=15149.71
       1    1158    1435
Encroach Node=14695.24
       1     925    1295
Encroach Node=14126.29
       1     825    1250
Encroach Node=12669.70
       1     900    1125
Encroach Node=11170.67
       1     665     933
Encroach Node=10399.98
       1     780     925
Encroach Node=9375.575
       1     937    1175
Encroach Node=8506.231
       1     700    1079
Encroach Node=7392.173
       1     850    1275
Encroach Node=6887.697
       1    1000 1186.48
Encroach Node=6784.822
       1     946    1145
Encroach Node=6761.167
       1  946.35    1145
Encroach Node=6737.510
       1     948    1145
Encroach Node=6632.963
       1     797    1050
Encroach Node=6259.743
       1    1010    1460
Encroach Node=5762.725
       1    2000    2250
Encroach Node=4911.257
       1 1904.28    2330
Encroach Node=3115.645
       1    1600 2382.61
Encroach Node=1796.011
       1    1250    1800
Encroach Node=202.802
       1     343     917
Computation Interval=1HOUR
Output Interval=1HOUR
Run HTab= 0
Run UNet= 0
Run PostProcess= 0
UNET Theta= 1
UNET ZTol= 0.02
UNET ZSATol= 0.1
UNET MxIter= 20
UNET MaxInSteps= 20
UNET DtIC= 0
UNET DtMin= 0
UNET MaxCRTS= 20
UNET WFStab= 2
UNET SFStab= 1
UNET WFX= 1
UNET SFX= 1
UNET Convert EG Bridges=-1
UNET Use Existing IB Tables=-1
Instantaneous Interval=1HOUR
DSS File=dss
Write IC File= 0
Write Velocity= 0
Write Detailed= 0

--- R102-00-00.p01 (plan) ---

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Plan Title=FEMA Effective June 2007
Program Version=3.13
Short Identifier=FEMAeff0607
Geom File=g03
Flow File=f02
Unsteady Bridges Friction Slope Method= 1
Encroach Param=-1 ,0,0, 0
UNET Theta Warmup= 1
UNET DSS MLevel= 4
UNET DZMax Abort= 100
UNET Froude Reduction=False
UNET Froude Limit= 1
UNET Froude Power= 10
Echo Input=False
Echo Output=False
Detailed Automatic Start=False, 10

--- R102-00-00.f04 (steady flow) ---

Flow Title=Floodway
Program Version=3.13
Number of Profiles= 2
Profile Names=1PCT_100yr,1PCTFloodway_100yrFW
River Rch & RM=R102-00-00,R102-00-00_0002 ,40526.82
    2272    2272
River Rch & RM=R102-00-00,R102-00-00_0002 ,38977.95
    2330    2330
River Rch & RM=R102-00-00,R102-00-00_0002 ,38365.48
    2498    2498
River Rch & RM=R102-00-00,R102-00-00_0002 ,36671.84
    2668    2668
River Rch & RM=R102-00-00,R102-00-00_0002 ,35064.35
    2813    2813
River Rch & RM=R102-00-00,R102-00-00_0002 ,33765.65
    2929    2929
River Rch & RM=R102-00-00,R102-00-00_0002 ,32782.46
    4306    4306
River Rch & RM=R102-00-00,R102-00-00_0002 ,31772.57
    4412    4412
River Rch & RM=R102-00-00,R102-00-00_0002 ,31294.23
    4662    4662
River Rch & RM=R102-00-00,R102-00-00_0002 ,30209.34
    4854    4854
River Rch & RM=R102-00-00,R102-00-00_0002 ,29416.59
    5079    5079
River Rch & RM=R102-00-00,R102-00-00_0002 ,28526.83
    5228    5228
River Rch & RM=R102-00-00,R102-00-00_0002 ,26857.31
    5367    5367
River Rch & RM=R102-00-00,R102-00-00_0002 ,25334.36
    5488    5488
River Rch & RM=R102-00-00,R102-00-00_0002 ,24048.65
    5667    5667
River Rch & RM=R102-00-00,R102-00-00_0002 ,22198.61
    5898    5898
River Rch & RM=R102-00-00,R102-00-00_0002 ,19885.91
    6090    6090
River Rch & RM=R102-00-00,R102-00-00_0002 ,18039.75
    7787    7787
River Rch & RM=R102-00-00,R102-00-00_0002 ,15149.71
    9674    9674
River Rch & RM=R102-00-00,R102-00-00_0002 ,8506.231
   10087   10087
River Rch & RM=R102-00-00,R102-00-00_0002 ,1796.011
   10187   10187
Boundary for River Rch & Prof#=R102-00-00,R102-00-00_0002 , 1
Up Type= 0
Dn Type= 3
Dn Slope=0.00067
DSS Import GetInterval= 0
DSS Import GetPeak= 0
DSS Import FillOption= 0

--- R102-00-00.f02 (steady flow) ---

Flow Title=FEMA Effective June 2007
Version=Version 3.0.1  Mar 2001
Number of Profiles= 4
Profile Names=10PCT_10yr,2PCT_50yr,1PCT_100yr,0.2PCT_500yr
River Rch & RM=R102-00-00,R102-00-00_0002    ,40526.82
    1254    1924    2272    3308
River Rch & RM=R102-00-00,R102-00-00_0002    ,38977.95
    1288    1973    2330    3384
River Rch & RM=R102-00-00,R102-00-00_0002    ,38365.48
    1387    2116    2498    3604
River Rch & RM=R102-00-00,R102-00-00_0002    ,36671.84
    1488    2262    2668    3827
River Rch & RM=R102-00-00,R102-00-00_0002    ,35064.35
    1575    2387    2813    4016
River Rch & RM=R102-00-00,R102-00-00_0002    ,33765.65
    1644    2486    2929    4166
River Rch & RM=R102-00-00,R102-00-00_0002    ,32782.46
    2450    3682    4306    6065
River Rch & RM=R102-00-00,R102-00-00_0002    ,31772.57
    2513    3777    4412    6209
River Rch & RM=R102-00-00,R102-00-00_0002    ,31294.23
    2661    3999    4662    6549
River Rch & RM=R102-00-00,R102-00-00_0002    ,30209.34
    2776    4171    4854    6809
River Rch & RM=R102-00-00,R102-00-00_0002    ,29416.59
    2910    4372    5079    7114
River Rch & RM=R102-00-00,R102-00-00_0002    ,28526.83
    2993    4498    5228    7313
River Rch & RM=R102-00-00,R102-00-00_0002    ,26857.31
    3071    4617    5367    7500
River Rch & RM=R102-00-00,R102-00-00_0002    ,25334.36
    3139    4720    5488    7662
River Rch & RM=R102-00-00,R102-00-00_0002    ,24048.65
    3239    4872    5667    7901
River Rch & RM=R102-00-00,R102-00-00_0002    ,22198.61
    3368    5069    5898    8210
River Rch & RM=R102-00-00,R102-00-00_0002    ,19885.91
    3475    5232    6090    8465
River Rch & RM=R102-00-00,R102-00-00_0002    ,18039.75
    4406    6619    7787   10966
River Rch & RM=R102-00-00,R102-00-00_0002    ,15149.71
    5569    8266    9674   14024
River Rch & RM=R102-00-00,R102-00-00_0002    ,8506.231
    5782    8616   10087   14623
River Rch & RM=R102-00-00,R102-00-00_0002    ,1796.011
    5833    8702   10187   14770
Boundary for River Rch & Prof#=R102-00-00,R102-00-00_0002    , 1
Up Type= 0
Dn Type= 3
Dn Slope=.00067
DSS Import GetInterval= 0
DSS Import GetPeak= 0
DSS Import FillOption= 0

--- R102-00-00.g03 (geometry) ---

Geom Title=R102-00-00 June 2007
Program Version=3.13

River Reach=R102-00-00      ,R102-00-00_0002
Reach XY= 30
     3210302.079    13922626.222     3210390.792    13920967.765
      3210839.84    13920863.113     3210449.228    13919332.767
     3208996.469    13918770.927     3207515.997    13916922.778
     3207704.694    13915575.333     3208824.054    13914063.922
     3208572.152    13912494.803      3209329.69    13911168.426
     3208772.758    13910090.286     3209150.152    13909371.221
     3208970.615     13908382.85     3208071.097    13907079.373
     3208176.438    13906335.575     3207519.661    13905982.913
     3208204.308    13903904.007     3208164.007    13903211.278
     3207748.066    13902993.803     3208021.051     13902499.54
     3207399.801    13902118.578       3207586.1    13900247.984
     3206878.924    13900038.112     3206468.306    13898435.181
     3206783.113     13897888.45     3206329.912    13898025.323
     3206189.237    13897683.141     3206856.112    13897236.784
     3207598.266    13897431.447     3208769.872    13896414.202

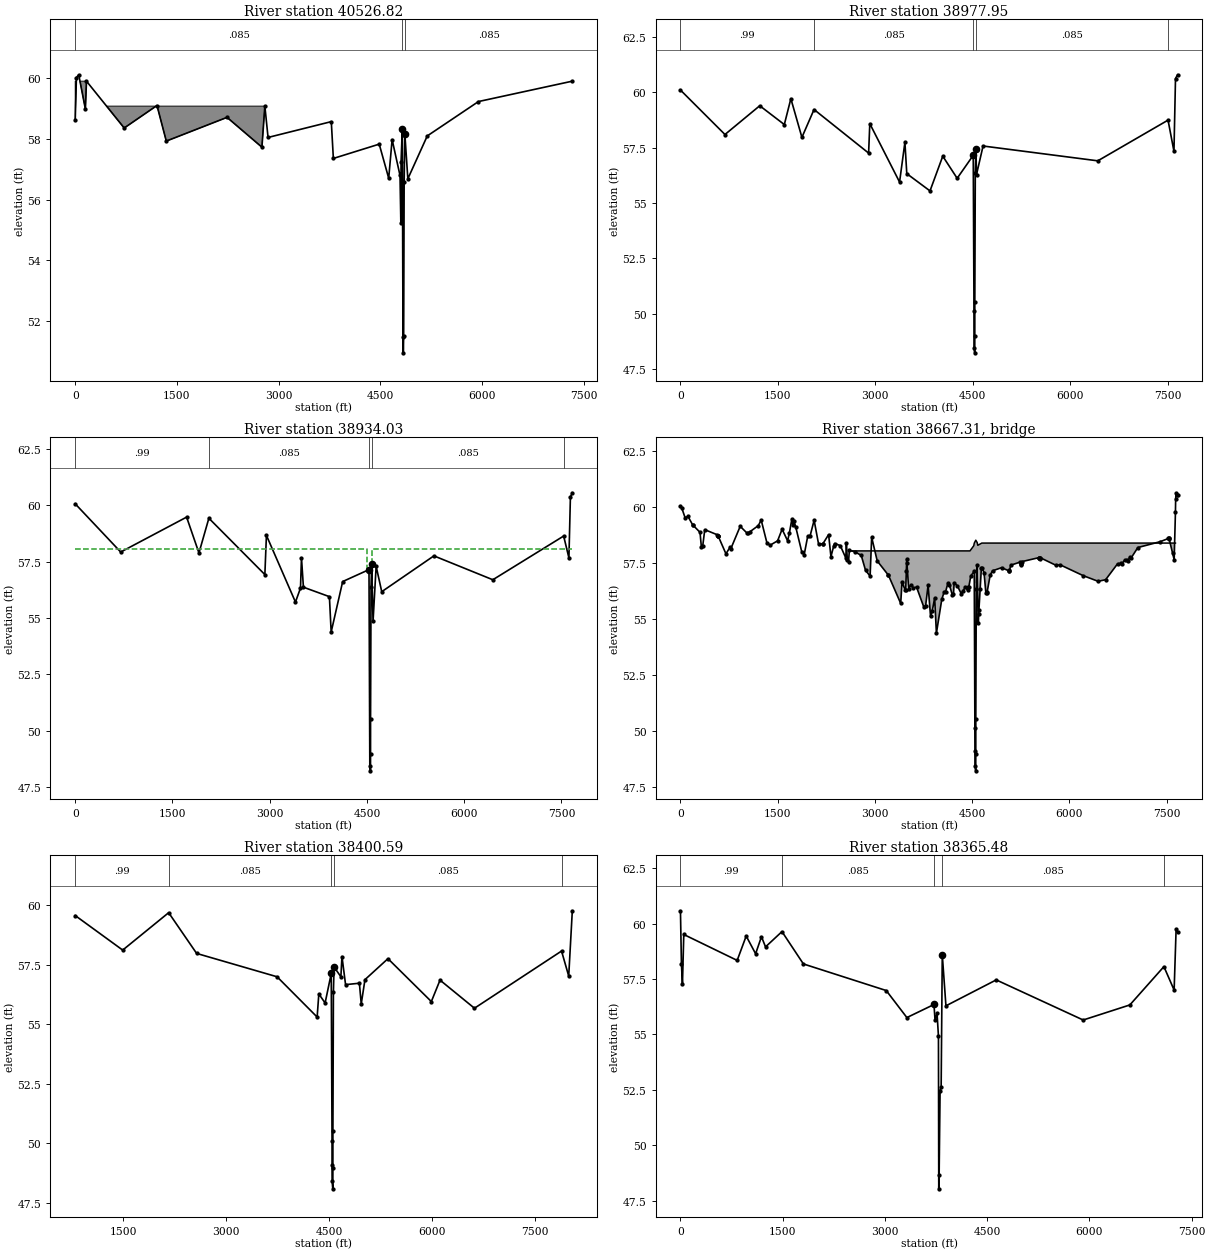
Type RM Length L Ch R = 1 ,40526.82,1525.96,1548.87,1570.05
BEGIN DESCRIPTION:
442v32
Cross section extended on LOB to contain 500 yr profile.
Blocked far LOB as 100yr elev does not extend to this area based on topography.
END DESCRIPTION:
XS GIS Cut Line= 5
     3215141.867    13922739.339     3213751.428    13922718.586
     3210331.435    13922602.457     3210243.612    13922608.032
     3207816.125    13922542.187
#Sta/Elev= 30
       0    58.6   17.68   60.01   51.98    60.1  150.22   58.97  166.28   59.89
  722.28   58.35 1205.59   59.09  1342.8   57.92 2238.58    58.7 2752.72   57.72
 2796.03   59.07 2843.12   58.04 3775.56   58.56 3806.01   57.35 4482.15   57.82
 4621.91    56.7 4672.35   57.97 4788.67   56.79 4800.85   55.24 4804.28   57.24
 4822.44   58.33 4832.59   51.49 4837.36   50.96 4842.42   51.52 4849.68   56.57
 4859.79   58.16 4903.97   56.68 5190.48   58.09 5945.41   59.22 7328.94   59.89
#Mann= 3 ,-1 , 0
       0    .085       0 4822.44    .045       0 4859.79    .085       0
#Block Obstruct= 2 ,-1
       0  166.28   59.89  166.28 2796.03   59.07
Bank Sta=4822.44,4859.79
Exp/Cntr=0.3,0.1

Type RM Length L Ch R = 1 ,38977.95,44.51,43.92,43.49
BEGIN DESCRIPTION:
Xsec 4/4 of Stroker Rd., 442s4u
END DESCRIPTION:
XS GIS Cut Line= 5
     3214890.256    13921281.709     3210570.916    13921108.453
     3210445.791    13921060.786     3210369.388     13921056.72
     3207251.263    13921119.193
#Sta/Elev= 30
       0   60.11  685.09    58.1 1220.63    59.4 1598.87   58.55 1699.57   59.72
 1869.58   57.97 2056.24   59.23 2896.39   57.26 2914.73   58.59 3372.83   55.95
 3455.16   57.75 3484.03   56.33 3841.36   55.55 4037.73   57.12 4259.41   56.12
 4507.01   57.16 4518.57   50.13 4519.66   48.45 4529.82   48.23 4530.87   48.99
 4531.09   50.55 4538.49   56.38 4548.24   57.43 4557.25   56.29  4658.1   57.58
 6424.36   56.91 7505.58   58.75 7596.62   57.34 7620.36   60.63 7651.97    60.8
#Mann= 5 ,-1 , 0
       0     .99       0 2056.24    .085       0 4507.01    .045       0
 4548.24    .085       0 7505.58     .99       0
Bank Sta=4507.01,4548.24
Exp/Cntr=0.5,0.3

Type RM Length L Ch R = 1 ,38934.03,535.01,533.44,159.08
BEGIN DESCRIPTION:
Xsec 3/4 of Stroker Rd., copy of 442s4u
Elevations adjusted based on slope between 442v30 and 442s4u
END DESCRIPTION:
XS GIS Cut Line= 6
     3214924.413    13921251.347     3210573.747    13921059.655
     3210453.491     13921021.99     3210390.162     13921013.73
     3210341.976    13921023.367     3207268.468    13921046.071
#Sta/Elev= 30
       0   60.06  701.75   57.92 1718.33   59.47 1908.47   57.88 2061.71   59.42
 2925.32   56.92  2949.4   58.66 3397.24    55.7 3474.91   56.32 3489.92   57.67
 3519.95   56.36 3920.83   55.94 3947.98   54.37 4125.46   56.61 4531.49   57.14
 4544.14   48.43  4554.3   48.21 4555.35   48.97 4555.57   50.53 4562.97   56.36
 4572.72   57.41 4593.91   54.84 4641.64   57.29 4728.02   56.16 5532.58   57.75
 6441.69   56.69 7533.94   58.63 7615.21   57.66  7638.1   60.36  7667.5   60.55
#Mann= 5 ,-1 , 0
       0     .99       0 2061.71    .085       0 4531.49    .045       0
 4572.72    .085       0 7533.94     .99       0
#XS Ineff= 2 , 0
       0 4508.33   58.05 4572.72       0   58.05
Permanent Ineff=
       F       F
Bank Sta=4531.49,4572.72
Exp/Cntr=0.5,0.3

Type RM Length L Ch R = 3 ,38667.31,,,
BEGIN DESCRIPTION:
442s4,  Stroker Road
Downstream section (2/4) stationing shifted 756.89' to the right to line up the u/s and d/s faces of the structure for floodways
END DESCRIPTION:
Bridge Culvert--1,0,-1,-1, 0
Deck Dist Width WeirC Skew NumUp NumDn MinLoCord MaxHiCord MaxSubmerge Is_Ogee
25,33.2,2.6,0, 12, 12, , , 0.95, 0, 0,0,,
 2607.45 4465.83 4523.59 4532.33 4532.33  4555.4 4577.59 4577.59 4586.24 4647.82
 7107.45  7634.9
   58.05   58.05   58.28    58.4    58.4   58.53   58.42   58.42    58.3    58.4
    58.4    58.4
       0       0       0       0    56.5   56.63   56.52       0       0       0
       0
  2638.3 4465.68 4523.44 4532.18 4532.18 4555.25 4577.44 4577.44 4586.09 4647.67
  7638.3 8030.39
   58.05   58.05   58.28    58.4    58.4   58.53   58.42   58.42    58.3    58.4
    58.4    58.4
       0       0       0       0    56.5   56.63   56.52       0       0       0
       0
BR Coef= 1 , 1 , 0 ,, 0 ,,,0.8,0,0,0,
WSPro=,,,, 1 ,,,, 0 ,,,, 0 ,,,,-1 ,-1 ,-1 , 0 , 0 , 0 , 0 , 0
BR U #Sta/Elev= 157
       0   60.06   17.85   59.99   70.94   59.54  116.85   59.59  186.67   59.22
  187.12   59.22  301.86   58.88   322.5   58.23  344.24   58.29   375.1      59
  560.71   58.78  574.47   58.71  575.75   58.71  577.81   58.71  582.53   58.71
  701.75   57.92  767.79   58.23  774.41   58.13  921.76   59.15 1032.25   58.83
 1044.27   58.83 1068.43    58.9 1200.44   59.18 1245.35   59.43 1335.42   58.39
 1385.94   58.31 1498.29    58.5 1568.06   59.02 1652.86    58.5 1681.43   58.87
 1718.33   59.47 1733.22   59.23 1751.06   59.37 1778.19   59.12 1870.91   58.01
 1908.47   57.88 1963.96   58.72 2000.43   58.73 2061.71   59.42 2131.41   58.34
 2198.78   58.38 2199.42   58.38 2285.47   58.78 2321.13   57.79  2364.7   58.28
 2377.27   58.38 2464.82   58.29 2550.84   57.73 2559.35    58.4 2574.04   57.64
 2592.54   57.57 2605.44   58.08 2687.89   58.01 2788.25   57.85 2854.73   57.18
 2925.32   56.92  2949.4   58.66    3035    57.6 3201.52   56.98 3208.15   56.96
 3397.24    55.7 3418.01   56.67 3462.76   56.31 3474.91   56.32 3485.01   57.17
 3489.92   57.67 3492.97   57.51 3519.95   56.36  3554.5   56.53 3591.67   56.39
 3641.47   56.43 3752.07   55.55 3782.05    55.6 3819.38   56.51 3857.69   55.12
 3884.93   55.38 3920.83   55.94 3947.98   54.37 4031.49   55.89 4069.67   56.23
 4090.51   56.23 4125.46   56.61  4149.7   56.51 4194.81   56.07 4210.62    56.1
 4221.64   56.62 4269.96   56.49 4330.23   56.14 4354.89   56.26 4396.13   56.42
 4430.49   56.28 4440.67   56.44 4447.15   56.43 4478.78   56.93 4531.49   57.14
 4543.05   50.11 4543.05   49.11 4544.14   48.43  4554.3   48.21 4555.35   48.97
 4555.57   50.53 4562.97   56.36 4572.72   57.41 4593.91   54.84  4600.5   55.22
 4603.83   55.41 4623.02   56.33 4641.64   57.29  4651.1    57.3 4682.99   57.07
 4710.41   56.18 4728.02   56.16  4730.9   56.22 4777.85   56.97 4813.52   57.16
 4953.94    57.3 5063.74   57.16 5069.95   57.21 5074.56   57.15 5093.93   57.41
 5240.82   57.55 5250.62   57.47 5255.42   57.43 5258.74   57.48 5265.96   57.57
 5532.58   57.75 5536.42   57.71 5538.04   57.71 5539.82   57.71 5542.47    57.7
  5553.5   57.74 5795.61    57.4 5854.35   57.43 6214.11   56.94 6441.69   56.69
 6557.88   56.76 6741.38   57.47 6789.63   57.49 6806.42   57.47 6850.94   57.63
 6884.11   57.66 6900.62   57.58 6928.03   57.76  6955.3   57.75 7054.86    58.2
  7396.5   58.46 7527.48   58.61 7530.78   58.61 7533.94   58.63 7537.96   58.58
 7590.83   57.95 7615.21   57.66  7634.9   59.78  7638.1   60.36 7644.53   60.65
 7664.13   60.57  7667.5   60.55
BR U #Mann= 5
       0     .99 2061.71    .085 4531.49    .045 4572.72    .085 7533.94     .99
BR D #Sta/Elev= 122
  801.05   59.56  805.03   59.49  819.62   59.43  873.14   59.14  914.81   58.94
 1081.66   58.93 1101.98   58.88 1173.66   58.84 1493.13   58.11 1648.81   59.07
 1651.64   59.13 1656.06   59.07 1821.25   58.44  1909.3   58.52 1946.58   59.57
 2032.54    58.9 2162.57   59.68 2168.56   59.68 2192.22   59.71 2422.17   58.73
 2570.24   57.97 2777.25   58.32 2894.34   57.63 2972.68   57.95 3157.84    57.5
 3207.53   57.41 3215.98    57.4 3226.74   57.34  3547.6   56.72 3550.24   56.72
 3742.31   56.99 3973.98   55.86 3997.39   55.82 4017.02   55.79 4209.15   55.88
 4249.06   55.91 4326.04    55.3 4350.53   56.27 4366.42   55.89 4429.08   55.89
 4442.04   55.89 4471.87   56.42 4473.19   56.42 4478.78   56.92 4531.49   57.13
 4543.05    50.1 4543.05    49.1 4544.14   48.21  4554.3   48.21 4555.35   48.96
 4555.57   50.52 4562.97   56.35 4572.72    57.4 4672.03   56.99 4673.77      57
  4687.7   57.84 4694.54   57.02 4740.13   56.66 4747.76   56.67 4752.55   56.68
 4810.52   56.68 4838.78    56.8 4880.29    56.9 4920.77   56.72 4940.86   56.72
 4941.57   56.72 4968.42   55.85 4977.37   56.18 4988.11   56.33  5000.5    56.5
 5022.82   56.87 5056.14   56.96 5120.58   57.14 5273.55    57.4 5274.94   57.41
 5357.68   57.75 5423.28   57.39 5569.51   56.85 5586.41   56.74 5588.98   56.75
 5589.31   56.74 5590.67   56.72 5593.94   56.77 5612.26   56.78 5774.17   56.81
 5802.16   56.79 5822.08   56.79 5989.82   55.95 6075.43    56.1 6116.33   56.85
 6144.36   56.83 6170.48   56.74 6174.83   56.53 6180.91   56.62 6194.15   56.67
 6216.17   56.79 6291.27   56.72  6316.2   56.59 6363.28   55.87 6509.76   55.89
 6588.86   55.68  6617.9   55.67 6891.93   56.39 7068.44   55.94 7342.59   56.39
 7401.85   56.64 7508.84   56.84 7560.17   57.08 7615.27   57.47 7706.18   57.35
 7792.74   57.28 7857.27    57.9  7864.5   57.93 7871.33   57.95 7877.79   58.01
 7886.83   58.07 7976.02   57.36 7991.44   57.02 8004.35   58.17 8030.39   59.79
  8042.4   59.85 8043.76   59.76
BR D #Mann= 5
  801.05     .99 2162.57    .085 4531.49    .045 4572.72    .085 7886.83     .99
BC Design=,, 0 ,, 0 ,,,,,,
BC HTab HWMax=60.65

Type RM Length L Ch R = 1 ,38400.59,35.04,35.1,53.94
BEGIN DESCRIPTION:
Xsec 2/4 of Stroker Rd., copy of 442s4u
Elevations asdjusted based on slope between 442v30 and 442s4u
Removed LIDAR high point (63+) at right channel bank.
Removed ineffective elevations due to the long distance from the d/s bridge face.  Flow is over the road and should be considered effective for this section.
END DESCRIPTION:
XS GIS Cut Line= 6
 3214572.869654913921056.1448584     3210947.363    13920920.986
     3210889.165    13920917.394     3210777.799    13920913.083
     3210376.161    13920908.772     3207335.597    13920780.723
#Sta/Elev= 30
  801.05   59.56 1493.13   58.11 2162.57   59.68 2570.24   57.97 3742.31   56.99
 4326.04    55.3 4350.53   56.27 4442.04   55.89 4531.49   57.13 4543.05    50.1
 4543.05    49.1 4544.14   48.42  4554.3   48.09 4555.35   48.96 4555.57   50.52
 4562.97   56.35 4572.72    57.4 4672.03   56.99  4687.7   57.84 4740.13   56.66
 4941.57   56.72 4968.42   55.85 5022.82   56.87 5357.68   57.75 5989.82   55.95
 6116.33   56.85  6617.9   55.67 7886.83   58.07 7991.44   57.02 8043.76   59.76
#Mann= 5 ,-1 , 0
  801.05     .99       0 2162.57    .085       0 4531.49    .045       0
 4572.72    .085       0 7886.83     .99       0
Bank Sta=4531.49,4572.72
Exp/Cntr=0.5,0.3

Type RM Length L Ch R = 1 ,38365.48,1826.06,1693.64,1328.31
BEGIN DESCRIPTION:
Xsec 1/4 of Stroker Rd., 442v30
END DESCRIPTION:
XS GIS Cut Line= 6
      3214632.18     13920898.39     3210882.242    13920882.387
     3210787.858    13920877.877     3210457.254    13920872.393
     3210051.126    13920851.766     3207341.387    13920742.513
#Sta/Elev= 30
       0   60.58   14.36   58.17   29.31   57.26   48.82   59.51  832.23   58.34
  964.55   59.44  1102.9   58.64 1188.55   59.41 1248.36   58.95 1489.45   59.64
 1803.99   58.18 3019.49   56.98 3322.23   55.76 3719.79   56.35 3735.79   55.63
 3764.71   55.96 3785.43   54.92    3790   48.03  3795.4   48.64 3809.22   52.43
 3825.16   52.64 3841.53    58.6 3895.26   56.29 4633.21   57.46 5908.99   55.65
 6593.73   56.33  7093.5   58.06 7243.48      57 7272.54   59.75 7293.71   59.63
#Mann= 5 ,-1 , 0
       0     .99       0 1489.45    .085       0 3719.79    .045       0
 3841.53    .085       0  7093.5     .99       0
Bank Sta=3719.79,3841.53
Exp/Cntr=0.3,0.1

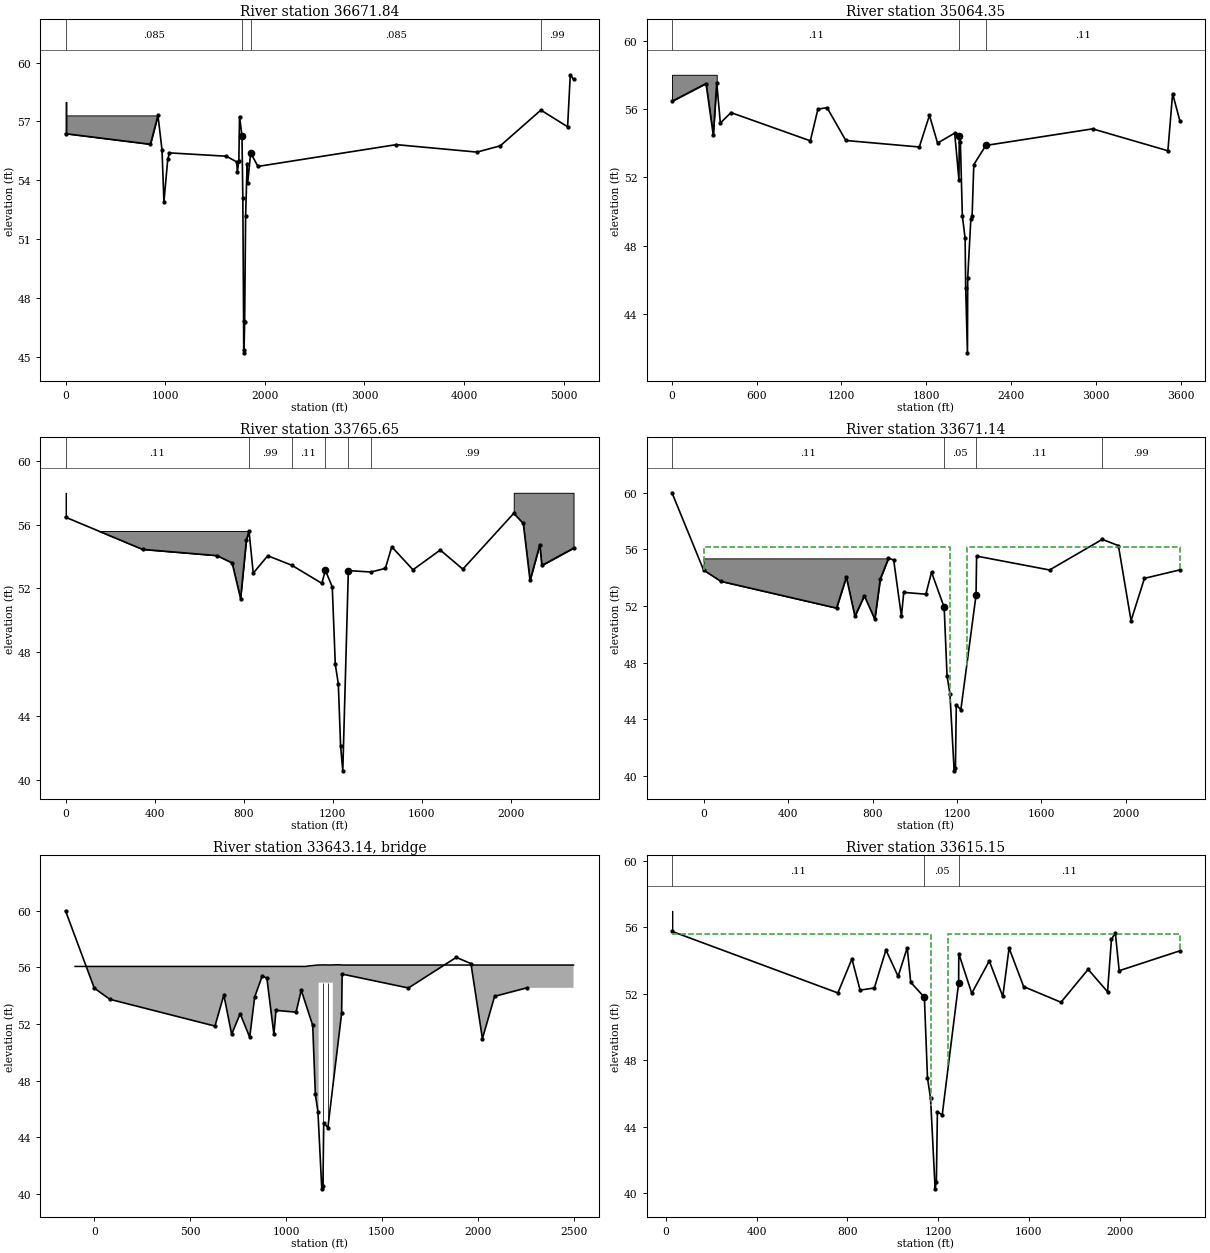
Type RM Length L Ch R = 1 ,36671.84,1534.16,1607.48,1447.25
BEGIN DESCRIPTION:
442v29
The 500yr Flood inundates the area on the extreme LOB, while the 100yr Flood cannot. Hence a block was added to the model in this area for the 100yr flood elevation.
END DESCRIPTION:
XS GIS Cut Line= 5
      3211707.67    13918155.708     3210393.625    13919229.797
     3210359.345    13919418.334     3209125.285    13920075.357
     3207380.301    13920564.329
#Sta/Elev= 30
       0   56.38  852.17   55.84  927.86   57.31  968.41   55.56  987.78   52.91
 1026.53   55.09 1043.73    55.4 1614.27   55.23 1719.05   54.94 1724.51   54.43
 1739.96      55 1746.45   57.25 1771.22   56.28 1779.57   53.12 1787.45   46.83
 1788.59   45.36 1791.36   45.21    1798   46.79 1807.63   52.18 1822.66   54.84
 1828.64   53.88 1858.48    55.4 1931.31   54.71 3319.68   55.82 4129.79   55.44
 4363.67   55.76  4771.1   57.58 5039.51   56.73 5066.06   59.38 5099.06   59.15
#Mann= 4 ,-1 , 0
       0    .085       0 1771.22    .045       0 1858.48    .085       0
  4771.1     .99       0
#Block Obstruct= 2 ,-1
       0      10      58      10  927.86   57.31
Bank Sta=1771.22,1858.48
Exp/Cntr=0.3,0.1

Type RM Length L Ch R = 1 ,35064.35,1239.11,1298.7,1253.43
BEGIN DESCRIPTION:
442v28
ROB and LOB blocks watershed divides, or areas not available for main stem flow or storage
END DESCRIPTION:
XS GIS Cut Line= 6
     3210559.391    13917367.536     3210302.213    13917578.671
     3209015.222    13918710.493     3208913.151    13918752.209
     3208244.239      13919103.9      3207634.13    13919412.621
#Sta/Elev= 30
       0   56.45  241.06   57.49  292.34   54.47  316.84   57.54   342.4   55.18
  417.74   55.79  979.61   54.14  1033.1   55.99 1097.59   56.08 1230.64   54.16
 1750.93   53.78 1822.77   55.63 1880.03   54.01 2001.35   54.59 2031.47   51.86
 2034.12   54.45 2041.62   54.05 2055.62   49.75 2075.12   48.45 2079.12   45.55
 2091.62   41.75 2093.62   46.15 2115.62   49.55 2124.62   49.75 2136.62   52.75
 2222.08   53.87 2977.64   54.84 3510.57   53.56 3543.97    56.9 3596.39   55.28
#Mann= 3 ,-1 , 0
       0     .11       0 2034.12    .045       0 2222.08     .11       0
#Block Obstruct= 2 , 0
       0  316.84      58 3552.97       0      58
Bank Sta=2034.12,2222.08
Exp/Cntr=0.3,0.1

Type RM Length L Ch R = 1 ,33765.65,80.94,94.51,82.18
BEGIN DESCRIPTION:
Xsec 4/4 of FM 2100, 442s3u
ROB block at watershed divide.
Block on LOB, 100yr elev. does not extend to this area.
END DESCRIPTION:
XS GIS Cut Line= 4
     3208967.664    13916826.949     3208238.191    13917766.253
     3208148.483    13917878.942     3207681.717     13918705.05
#Sta/Elev= 30
       0   56.47  346.03   54.45   680.6   54.06   748.4    53.6  786.38   51.36
  812.35   55.02  824.36    55.6  843.36   52.96  908.47   54.05  1015.8   53.46
 1151.59   52.32 1167.12   53.14 1198.29    52.1 1211.95   47.24 1225.53   46.01
 1235.74   42.12  1245.6   40.56 1270.59   53.12 1372.49   53.03 1436.76   53.26
 1465.69   54.61 1560.87   53.17 1683.42   54.41 1784.89   53.21 2013.49   56.71
 2056.23   56.08 2086.72    52.5 2130.55   54.74 2139.65   53.44 2282.19   54.53
#Mann= 6 ,-1 , 0
       0     .11       0  824.36     .99       0  1015.8     .11       0
 1167.12    .045       0 1270.59     .11       0 1372.49     .99       0
#Block Obstruct= 3 ,-1
       0       2      58       2  824.36    55.6 2013.49 2282.19      58
Bank Sta=1167.12,1270.59
Exp/Cntr=0.5,0.3

Type RM Length L Ch R = 1 ,33671.14,55.99,55.99,59.95
BEGIN DESCRIPTION:
Xsec 3/4 of FM 2100, copy of 442s3u
Elevations adjusted based on slope between 442v28 and 442v28
XS extended on LOB.  Block on LOB, 100yr elev. does not extend to this area.
Block on ROB at watershed divide
survey points of piers added RS 1192.8, el 40.57; RS
1218.48, el 44.69
block in ROB is area where water will not be stored or flowing
END DESCRIPTION:
XS GIS Cut Line= 6
 3208822.953210213916567.1091499      3208751.13    13916698.796
     3208360.292    13917415.392     3208178.778    13917727.436
     3208164.738    13917750.492      3207668.46    13918678.536
#Sta/Elev= 30
    -150      60       0   54.54   81.25   53.75  629.51   51.86  675.96   54.05
  716.57   51.28  761.01   52.73  810.86   51.07  836.66   53.91  875.37   55.37
   900.2   55.26  936.98   51.28  947.95   52.97 1052.72   52.84 1079.67   54.39
 1139.45   51.91 1153.11   47.05 1166.69   45.82 1186.76   40.37  1192.8   40.57
 1196.86   45.02 1218.48   44.69  1290.4   52.77 1293.02   55.53 1638.64   54.55
 1888.32   56.71 1964.85   56.27 2024.63   50.97 2088.25   53.96 2256.65   54.56
#Mann= 4 ,-1 , 0
    -150     .11       0 1139.45     .05       0  1290.4     .11       0
 1888.32     .99       0
#XS Ineff= 2 , 0
       0    1169   56.17    1246       0   56.17
Permanent Ineff=
       F       F
#Block Obstruct= 2 , 0
       0  875.37   55.37 1961.01       0      58
Bank Sta=1139.45,1290.4
Exp/Cntr=0.5,0.3

Type RM Length L Ch R = 3 ,33643.14,,,
BEGIN DESCRIPTION:
442s3,  FM 2100
Downstream section (2/4) stationing shifted 27.43' to the right to line up the u/s and d/s faces of the structure for floodways
END DESCRIPTION:
Bridge Culvert--1,0,-1,-1, 0
Deck Dist Width WeirC Skew NumUp NumDn MinLoCord MaxHiCord MaxSubmerge Is_Ogee
7.5,41,2.6,0, 13, 13, , , 0.95, 0, 0,0,,
    -100 1102.79 1121.08 1158.27 1170.25 1170.25 1200.38 1233.31 1244.22 1244.22
 1270.68 1298.62    2500
   56.07   56.07   56.11   56.16   56.17   56.17   56.18   56.17   56.18   56.18
   56.19   56.17   56.17
       0       0       0       0       0   54.92   54.93   54.92   54.93       0
       0       0       0
   27.43 1102.22 1120.51  1157.7 1169.68 1169.68 1199.81 1232.74 1243.65 1243.65
 1270.11 1298.05 2527.43
   56.07   56.07   56.11   56.16   56.17   56.17   56.18   56.17   56.18   56.18
   56.19   56.17   56.17
       0       0       0       0       0   54.92   54.93   54.92   54.93       0
       0       0       0
Pier Skew, UpSta & Num, DnSta & Num=  ,1192.81, 4 ,1192.24, 4 , 3 , 3 , 0 ,0,
     1.3     1.3     2.3     2.3
      35   52.61   52.61   54.94
     1.3     1.3     2.3     2.3
      35   52.61   52.61   54.94
Pier Skew, UpSta & Num, DnSta & Num=  ,1218.48, 4 ,1217.91, 4 , 3 , 3 , 0 ,0,
     1.3     1.3     2.3     2.3
      35   52.64   52.64   54.94
     1.3     1.3     2.3     2.3
      35   52.64   52.64   54.94
BR Coef= 1 , 1 , 0 ,, 0 ,,,0.8,0,2,0,
WSPro=,,,, 1 ,,,, 0 ,,,, 0 ,,,,-1 ,-1 ,-1 , 0 , 0 , 0 , 0 , 0
BC Design=,, 0 ,, 0 ,,,,,,
BC HTab HWMax=60

Type RM Length L Ch R = 1 ,33615.15,94.35,94.35,108.08
BEGIN DESCRIPTION:
Xsec 2/4 of FM 2100, copy of 442s3u
Elevations adjusted based on slope between 442v28 and 442v28
survey points of piers added:  RS 1164.81, el 40.69; RS 1190.48, el 44.69
block in ROB is area where water will not be stored or flowing
END DESCRIPTION:
XS GIS Cut Line= 4
     3208676.006    13916672.282     3208138.386    13917688.813
     3208124.346    13917711.869     3207615.431    13918643.183
#Sta/Elev= 30
   27.43   55.76  758.37   52.05  820.15    54.1  856.26   52.22  919.04   52.35
  970.06   54.64 1023.77   53.05 1063.75   54.77 1079.31   52.69 1139.45   51.79
 1153.11   46.93 1166.69    45.7 1186.76   40.25 1192.24   40.69 1196.86    44.9
 1217.91   44.69  1290.4   52.65    1291   54.42 1348.14   52.03 1425.35   53.98
 1484.89   51.84 1512.61   54.75 1576.86   52.43 1741.29   51.49 1860.94   53.47
 1946.41   52.12  1963.5   55.27  1980.6   55.68 1997.69   53.39 2265.66   54.59
#Mann= 3 ,-1 , 0
   27.43     .11       0 1139.45     .05       0  1290.4     .11       0
#XS Ineff= 2 , 0
       0 1168.43    55.6 1245.43       0    55.6
Permanent Ineff=
       F       F
#Block Obstruct= 2 , 0
   27.43   29.43      57  1980.6   27.43      57
Bank Sta=1139.45,1290.4
Exp/Cntr=0.5,0.3

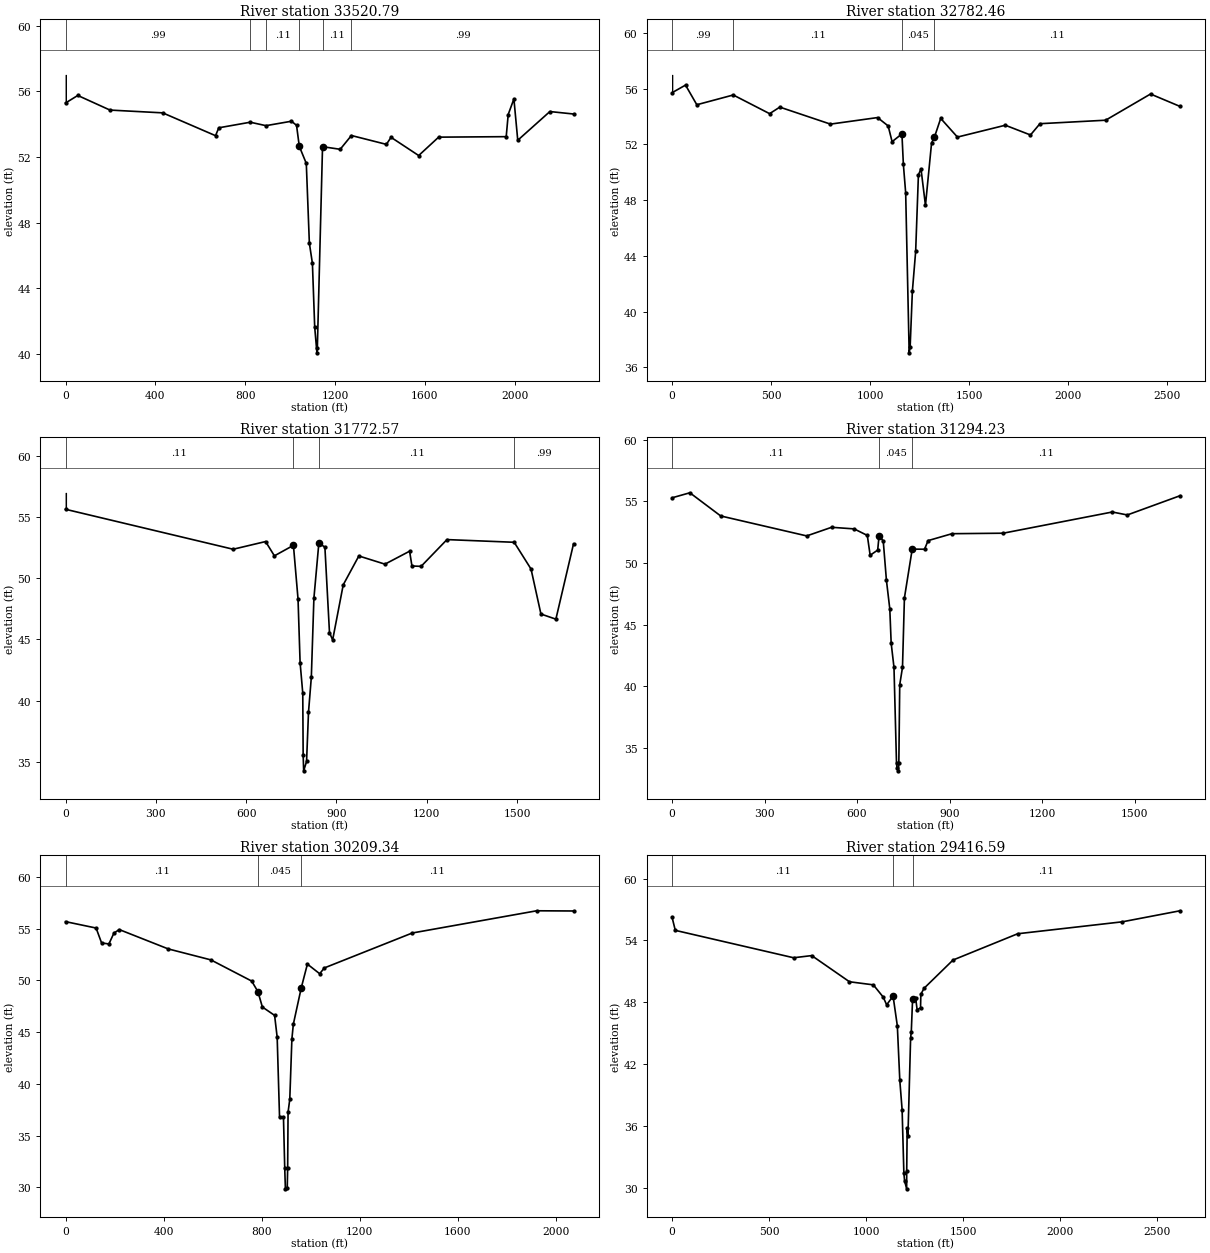
Type RM Length L Ch R = 1 ,33520.79,674.06,738.33,672.75
BEGIN DESCRIPTION:
Xsec 1/4 of FM 2100, copy of 442s3u
Elevations adjusted based on slope between 442v28 and 442v28
block in ROB is area where water will not be stored or flowing.
Set n = 0.99 in far LOB due to topography - the flow is not effective in this area.
END DESCRIPTION:
XS GIS Cut Line= 4
     3208605.301    13916641.348      3208076.03    13917618.346
      3208061.99    13917641.402     3207518.211    13918625.507
#Sta/Elev= 30
       0   55.28   54.67   55.74  198.01   54.85  432.83   54.68  668.09   53.29
  682.72   53.77  822.75   54.11  892.74    53.9 1006.28   54.17 1028.91   53.92
 1041.16   52.64 1072.33    51.6 1085.99   46.74 1099.57   45.51 1109.78   41.62
 1119.64   40.06 1121.48   40.33 1144.63   52.62 1223.28   52.46 1273.26    53.3
 1429.05   52.76 1449.67   53.19  1572.8   52.08 1661.63    53.2 1962.61   53.23
 1971.49   54.58 1996.89   55.53 2014.02   53.01 2157.06   54.76 2262.49   54.61
#Mann= 6 ,-1 , 0
       0     .99       0  822.75     .99       0  892.74     .11       0
 1041.16    .045       0 1144.63     .11       0 1273.26     .99       0
#Block Obstruct= 2 , 0
       0       2      57 1996.89       0      57
Bank Sta=1041.16,1144.63
Exp/Cntr=0.3,0.1

Type RM Length L Ch R = 1 ,32782.46,936,1009.89,983.23
BEGIN DESCRIPTION:
442v27
block in ROB is area where water will not be stored or flowing
END DESCRIPTION:
XS GIS Cut Line= 4
     3208471.765    13916275.835     3207698.278    13917115.818
     3207620.815    13917222.505     3206930.106    13918311.625
#Sta/Elev= 30
       0   55.71   68.38   56.26  125.33   54.85  309.25   55.55  492.63   54.21
  544.11   54.68  799.48   53.46  1037.3   53.93  1090.8   53.33 1110.68    52.2
 1160.25   52.76 1167.56   50.57 1179.16   48.53 1196.82   37.05 1201.64   37.45
 1212.95   41.47 1229.56   44.33 1243.48   49.82 1256.48   50.25 1279.03   47.63
 1309.85   52.11 1323.96   52.51 1355.93   53.87 1440.33   52.53    1682   53.38
 1808.88   52.68 1856.68   53.49 2188.05   53.74  2414.6   55.62 2563.38   54.73
#Mann= 4 ,-1 , 0
       0     .99       0  309.25     .11       0 1160.25    .045       0
 1323.96     .11       0
#Block Obstruct= 2 , 0
       0       2      57  2414.6       0      57
Bank Sta=1160.25,1323.96
Exp/Cntr=0.3,0.1

Type RM Length L Ch R = 1 ,31772.57,449.68,478.33,468.36
BEGIN DESCRIPTION:
442v26
ROB block at roadway
END DESCRIPTION:
XS GIS Cut Line= 4
     3208343.866    13916143.542     3207627.427    13916256.977
     3207518.928    13916274.934     3206678.665    13916418.704
#Sta/Elev= 30
       0   55.65  556.98   52.38  664.71   53.01  693.97   51.84  757.21    52.7
  772.52    48.3  779.36   43.11  788.21   40.61  789.52   35.56  791.19   34.25
  800.87   35.02  807.26   39.04  816.66    41.9  825.22   48.37  841.67   52.89
  861.77   52.55  876.99   45.56  887.49   44.96  922.65   49.47  974.54   51.83
 1061.29   51.16 1143.17   52.22 1150.92   51.01 1181.35   50.98 1267.34   53.17
 1490.61   52.95 1546.58   50.76 1579.45   47.08 1629.11   46.66 1687.81   52.83
#Mann= 4 ,-1 , 0
       0     .11       0  757.21    .045       0  841.67     .11       0
 1490.61     .99       0
#Block Obstruct= 2 , 0
       0       2      57    1685       0      57
Bank Sta=757.21,841.67
Exp/Cntr=0.3,0.1

Type RM Length L Ch R = 1 ,31294.23,1054.98,1084.9,1064.11
BEGIN DESCRIPTION:
442v25
END DESCRIPTION:
XS GIS Cut Line= 4
     3208315.401    13916081.868     3207695.074    13915846.067
     3207571.762    13915803.266     3206773.548     13915503.08
#Sta/Elev= 30
       0   55.28   57.97   55.69  157.94   53.81  436.79   52.19  517.49   52.89
  590.57   52.76  633.24   52.23  642.45   50.62  666.87   51.04  671.45   52.22
  684.92   51.77  695.25   48.58  706.14   46.27  710.57   43.49  719.72   41.52
  727.87   33.77  729.56   33.32  734.12   33.13  735.42   33.77  738.35   40.12
  747.28   41.52  753.55   47.16  778.82   51.12   818.7   51.11  830.35   51.81
  907.76   52.37 1073.62   52.41 1427.42   54.13 1476.04   53.89 1646.95   55.45
#Mann= 3 ,-1 , 0
       0     .11       0  671.45    .045       0  778.82     .11       0
Bank Sta=671.45,778.82
Exp/Cntr=0.3,0.1

Type RM Length L Ch R = 1 ,30209.34,773.43,792.74,735.5
BEGIN DESCRIPTION:
442v24
END DESCRIPTION:
XS GIS Cut Line= 4
     3208994.401    13915585.379     3208343.597    13915105.333
     3208247.064    13915039.386     3207292.549    13914404.171
#Sta/Elev= 30
       0   55.69  124.75   55.07  147.15   53.63  176.99   53.53  197.63   54.59
  219.44   54.92  419.06   53.05  592.81   51.99  759.35   49.94  784.75   48.92
  802.95   47.43  852.86   46.62  863.31   44.51  873.02   36.77  888.96    36.8
  894.17   31.84  896.86   29.84  904.41   29.94  906.14    31.9  907.74   37.25
  914.74    38.5  923.35   44.34  929.23   45.76  961.61   49.29  986.56   51.58
 1036.72   50.65 1055.64   51.21 1414.26   54.59 1921.83   56.74 2072.16   56.72
#Mann= 3 ,-1 , 0
       0     .11       0  784.75    .045       0  961.61     .11       0
Bank Sta=784.75,961.61
Exp/Cntr=0.3,0.1

Type RM Length L Ch R = 1 ,29416.59,883.82,889.76,863.04
BEGIN DESCRIPTION:
442v23
END DESCRIPTION:
XS GIS Cut Line= 2
     3209687.925    13914835.996     3207262.952    13913847.285
#Sta/Elev= 30
       0   56.28   17.08   54.97  626.97   52.31  720.37   52.52  914.95   49.98
 1037.96   49.68 1088.93   48.49 1106.65   47.74 1139.71   48.59 1161.68    45.7
 1174.44    40.4 1186.31   37.56 1195.28   31.45 1198.91   30.67 1209.71   29.88
    1210   31.58 1212.44   35.77 1216.36      35  1230.1   44.51 1233.68   45.15
 1240.31    48.3 1256.03   48.38 1263.87   47.25 1281.25   47.46 1282.91   48.76
 1299.02   49.34 1448.76   52.09    1782   54.64 2321.76    55.8 2618.79   56.87
#Mann= 3 ,-1 , 0
       0     .11       0 1139.71    .045       0 1240.31     .11       0
Bank Sta=1139.71,1240.31
Exp/Cntr=0.3,0.1