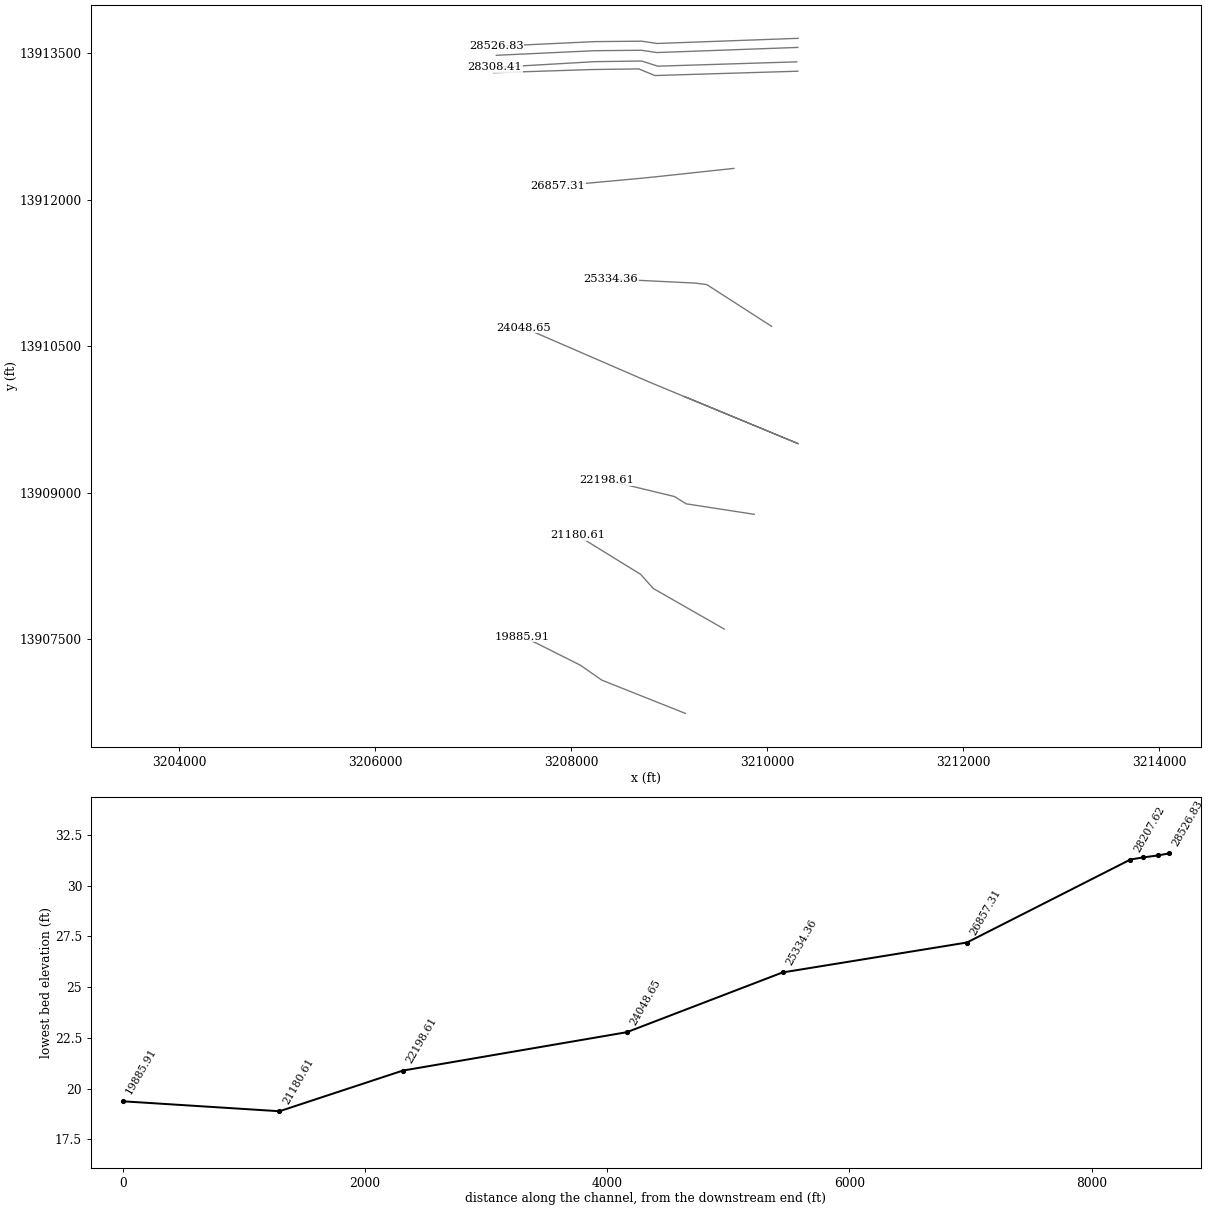
HEC-RAS study R102-00-00.prj: R102-00-00

--- R102-00-00.g03 (geometry) --- (continued)

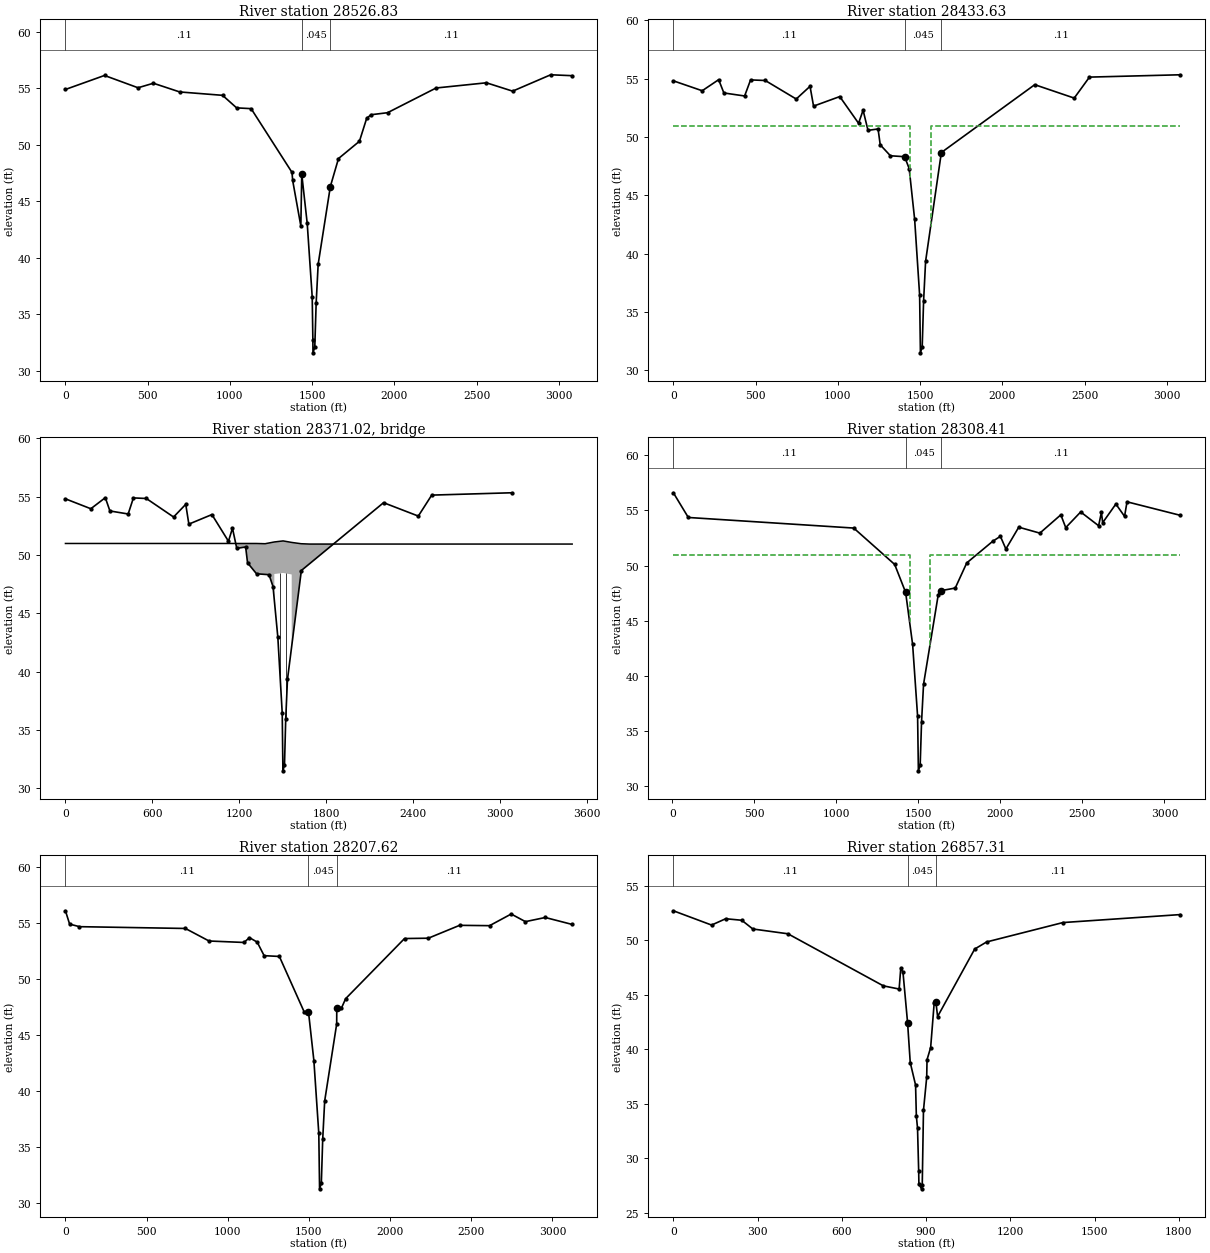
Type RM Length L Ch R = 1 ,28526.83,92.92,93.21,92.74
BEGIN DESCRIPTION:
Xsec 4/4 of Foley Road, copy of 442s2u
Elevations adjusted based on slope between 442v23 and 442v22
END DESCRIPTION:
XS GIS Cut Line= 6
     3210313.571    13913655.234     3208897.135    13913603.364
     3208875.501    13913602.572     3208717.199    13913626.008
     3208239.628    13913621.566     3207236.324    13913574.431
#Sta/Elev= 30
       0   54.91  237.54   56.15  441.35   55.06  534.89   55.46  694.62   54.69
   955.3   54.39 1040.72   53.28  1129.1   53.21 1377.69   47.56 1381.63   46.85
 1431.31   42.82 1436.96   47.39 1470.15   43.04 1500.48   36.53 1504.47   32.74
 1505.26   31.58 1516.13   32.09 1524.58   36.02 1536.72   39.43 1610.69   46.31
 1660.24   48.79 1787.62   50.32 1831.37   52.34 1857.44   52.67 1958.53   52.85
 2253.85   55.04 2559.71    55.5 2719.12   54.76 2950.54   56.21 3081.06   56.13
#Mann= 3 ,-1 , 0
       0     .11       0 1436.96    .045       0 1610.69     .11       0
Bank Sta=1436.96,1610.69
Exp/Cntr=0.5,0.3

Type RM Length L Ch R = 1 ,28433.63,131.69,125.22,112.86
BEGIN DESCRIPTION:
Xsec 3/4 of Foley Road, 442s2u
END DESCRIPTION:
XS GIS Cut Line= 6
     3210311.747    13913562.185      3208895.31    13913510.315
     3208873.677    13913509.523     3208715.375     13913532.96
     3208237.803    13913528.518     3207234.499    13913481.382
#Sta/Elev= 30
       0   54.82  175.36   53.97  275.42   54.92  307.14   53.78  433.31   53.52
  469.51    54.9  558.69   54.85  746.95   53.26  830.99   54.35  852.41   52.65
 1011.68   53.47  1126.1   51.18 1153.68    52.3  1183.4   50.57 1244.71   50.69
 1257.84   49.33 1319.76   48.39 1406.16   48.31 1433.88   47.29 1467.07   42.94
  1497.4   36.43 1502.18   31.48 1513.05   31.99  1521.5   35.92 1533.64   39.33
 1629.51   48.67 2197.34   54.49 2437.34   53.34 2530.01   55.14 3081.06   55.34
#Mann= 3 ,-1 , 0
       0     .11       0 1406.16    .045       0 1629.51     .11       0
#XS Ineff= 2 , 0
       0    1441   50.97    1564       0   50.94
Permanent Ineff=
       F       F
Bank Sta=1406.16,1629.51
Exp/Cntr=0.5,0.3

Type RM Length L Ch R = 3 ,28371.02,,,
BEGIN DESCRIPTION:
442s2,  Foley Road
Downstream section (2/4) stationing shifted 6.08' to the right to line up the u/s and d/s faces of the structure for floodways
END DESCRIPTION:
Bridge Culvert--1,0,-1,-1, 0
Deck Dist Width WeirC Skew NumUp NumDn MinLoCord MaxHiCord MaxSubmerge Is_Ogee
39.5,46,2.6,0, 11, 11, , , 0.95, 0, 0,0,,
       0    1318 1379.09 1442.82 1442.82 1503.57 1562.74 1562.74  1627.7 1685.21
    3500
   50.99   50.99   50.97   51.12   51.12   51.21   51.08   51.08   50.97   50.94
   50.94
       0       0       0       0   48.37   48.46   48.33       0       0       0
       0
    6.08 1323.08 1384.17  1447.9  1447.9 1508.65 1567.82 1567.82 1632.78 1690.29
 3506.08
   50.99   50.99   50.97   51.12   51.12   51.21   51.08   51.08   50.97   50.94
   50.94
       0       0       0       0   48.37   48.46   48.33       0       0       0
       0
Pier Skew, UpSta & Num, DnSta & Num=  ,1482.46, 4 ,1487.54, 4 , 3 , 3 , 0 ,0,
     1.3     1.3       2       2
      30   46.38   46.38   48.46
     1.3     1.3       2       2
      30   46.38   46.38   48.46
Pier Skew, UpSta & Num, DnSta & Num=  ,1522.11, 4 ,1527.19, 4 , 3 , 3 , 0 ,0,
     1.3     1.3       2       2
      30   46.38   46.38   48.46
     1.3     1.3       2       2
      30   46.38   46.38   48.46
BR Coef= 1 , 1 , 0 ,, 0 ,,,0.8,0,2,0,
WSPro=,,,, 1 ,,,, 0 ,,,, 0 ,,,,-1 ,-1 ,-1 , 0 , 0 , 0 , 0 , 0
BC Design=,, 0 ,, 0 ,,,,,,
BC HTab HWMax=55.9

Type RM Length L Ch R = 1 ,28308.41,98.76,100.78,89.3
BEGIN DESCRIPTION:
Xsec 2/4 of Foley Road, copy of 442s2u
Elevations adjusted based on slope between 442v23 and 442v22
END DESCRIPTION:
XS GIS Cut Line= 5
     3210300.458    13913414.359     3208882.331    13913369.896
     3208716.988    13913422.819     3208240.116    13913416.258
     3207222.086    13913357.171
#Sta/Elev= 30
    6.08    56.6   97.18   54.36 1105.61    53.4 1355.28    50.1 1421.97   47.57
 1464.69   42.84 1495.02   36.33  1499.8   31.38 1510.67   31.89 1519.12   35.82
 1531.26   39.23 1621.06   47.37 1640.53   47.73 1724.55   47.96 1794.73   50.24
 1952.93    52.2 1999.82   52.65 2033.27    51.5 2111.78   53.48  2240.3   52.94
 2368.09    54.6 2398.06   53.44 2489.25   54.86 2598.55   53.61 2615.51   54.82
 2623.31   53.89 2703.73   55.58 2756.73   54.46 2771.72   55.78 3095.17   54.56
#Mann= 3 ,-1 , 0
    6.08     .11       0 1421.97    .045       0 1640.53     .11       0
#XS Ineff= 2 , 0
       0 1446.08   50.97 1569.08       0   50.94
Permanent Ineff=
       F       F
Bank Sta=1421.97,1640.53
Exp/Cntr=0.5,0.3

Type RM Length L Ch R = 1 ,28207.62,1190.71,1350.32,1233.98
BEGIN DESCRIPTION:
Xsec 1/4 of Foley Road, copy of 442s2u
Elevations adjusted based on slope between 442v23 and 442v22
END DESCRIPTION:
XS GIS Cut Line= 5
     3210312.158    13913318.413     3208851.909     13913273.95
      3208688.54    13913342.046     3208211.668    13913335.484
     3207205.171    13913302.596
#Sta/Elev= 30
       0   56.12    25.7   54.93   86.59    54.7  738.93   54.54   884.7   53.42
  1099.7   53.29 1133.94   53.72 1181.31   53.32 1224.12   52.11 1317.99   52.04
 1470.72   47.09 1497.42   47.09 1530.61   42.74 1560.94   36.23 1565.72   31.28
 1576.59   31.79 1585.04   35.72 1597.18   39.13 1671.15   46.01 1671.65   47.42
    1700   47.41 1726.39   48.27 2089.12   53.64 2235.71   53.67 2428.57   54.82
 2613.14   54.79 2746.25   55.83 2834.02   55.15 2956.24   55.52 3121.87    54.9
#Mann= 3 ,-1 , 0
       0     .11       0 1497.42    .045       0 1671.15     .11       0
Bank Sta=1497.42,1671.65
Exp/Cntr=0.3,0.1

Type RM Length L Ch R = 1 ,26857.31,1345.54,1522.95,1241.91
BEGIN DESCRIPTION:
442v22
END DESCRIPTION:
XS GIS Cut Line= 4
     3209658.164     13912322.57     3208896.258    13912240.131
     3208696.374     13912219.74     3207862.465       13912143.
#Sta/Elev= 30
       0    52.7  136.12   51.39  186.37   51.97  243.57   51.83     283   51.03
  407.99   50.59  747.93 45.8124  804.12 45.5216  809.83 47.4245  817.75 47.0757
   834.2 42.4273  843.67 38.7738  862.65 36.7158   865.4 33.8818  869.61 32.7571
  873.73 28.7969  874.52 27.6298  883.88 27.1944  886.37 27.5059  890.79 34.3994
   902.3 37.4288  903.45  39.039  916.33 40.1516  928.97  44.256  934.84 44.3767
  941.08  42.997 1073.22   49.19 1115.62   49.84 1387.66   51.62 1804.71   52.35
#Mann= 3 ,-1 , 0
       0     .11       0   834.2    .045       0  934.84     .11       0
Bank Sta=834.2,934.84
Exp/Cntr=0.3,0.1

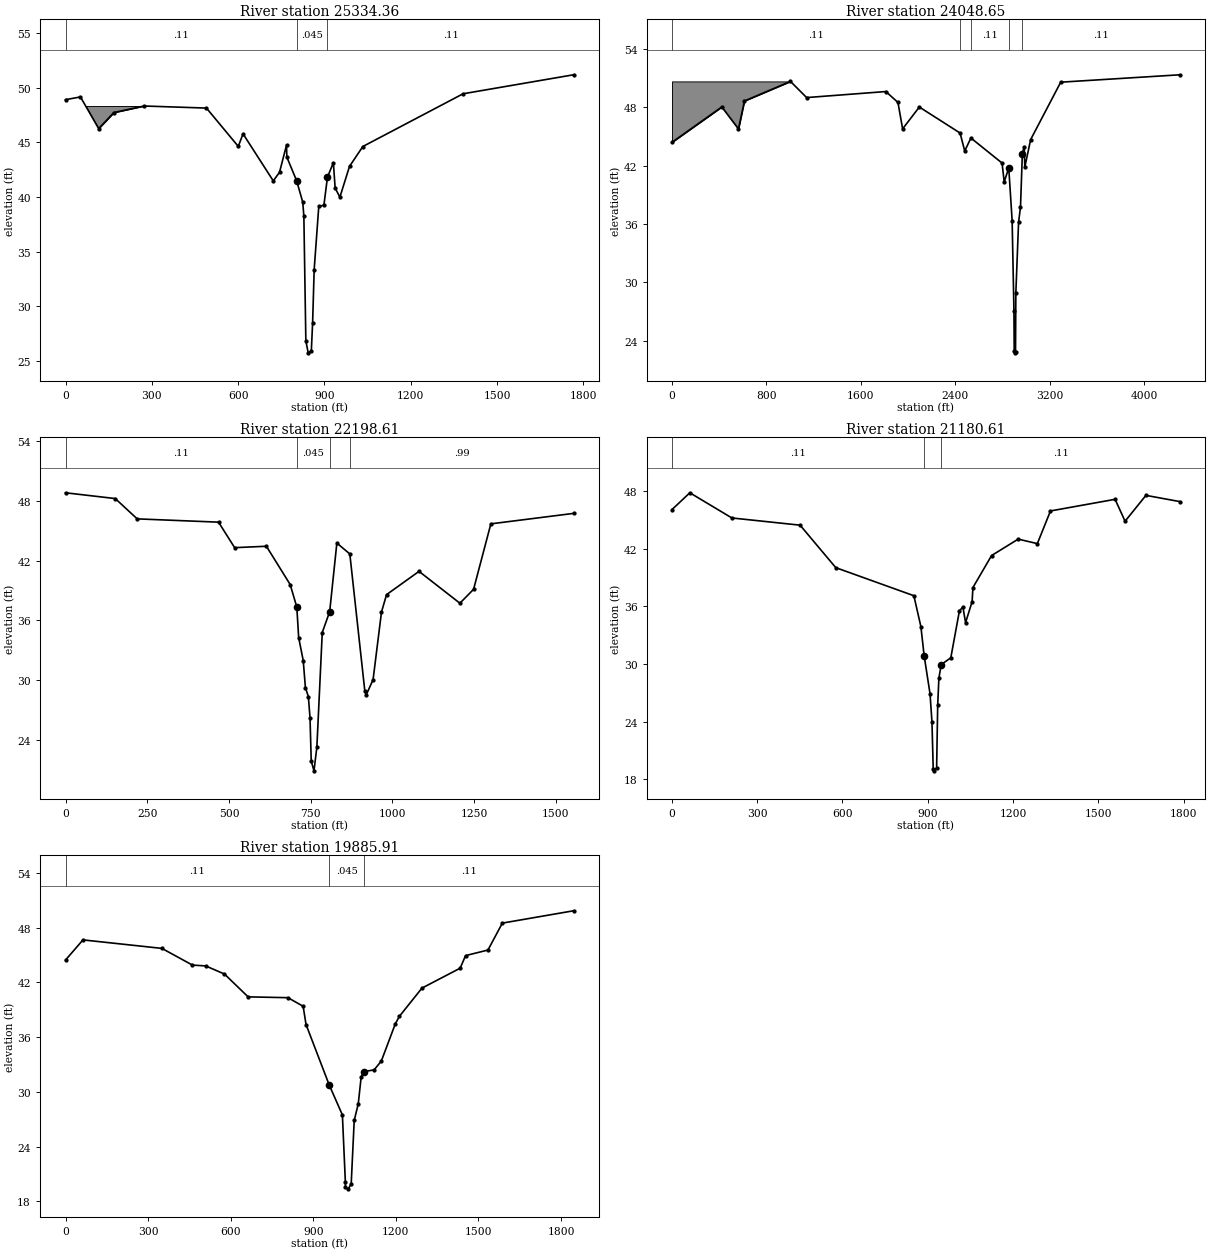
Type RM Length L Ch R = 1 ,25334.36,1165.41,1285.71,1153.24
BEGIN DESCRIPTION:
442v21
block in left overbank is area where water will not be stored or flowing
END DESCRIPTION:
XS GIS Cut Line= 4
     3210043.042    13910704.473     3209382.596    13911131.676
     3209263.863    13911147.167     3208405.165    13911189.285
#Sta/Elev= 30
       0   48.91   51.95   49.16  115.27   46.26  167.95   47.73  272.88   48.33
  489.96   48.14  600.59   44.63  617.15   45.78  722.26   41.47  743.96   42.26
  768.36   44.76  769.41   43.65  803.34   41.49  824.74   39.52  828.58   38.22
  835.48   26.82  843.61   25.72   854.5   25.88     859   28.47  864.39   33.33
  880.43   39.14  898.25   39.24  910.58   41.81  931.11   43.14  937.34   40.81
  953.82   39.98  987.23    42.8 1033.61   44.62 1382.05   49.45 1766.04   51.19
#Mann= 3 ,-1 , 0
       0     .11       0  803.34    .045       0  910.58     .11       0
#Block Obstruct= 2 , 0
       0  272.88   48.33               0
Bank Sta=803.34,910.58
Exp/Cntr=0.3,0.1

Type RM Length L Ch R = 1 ,24048.65,1395.6,1850.05,1457.48
BEGIN DESCRIPTION:
442v20
block in left overbank is area where water will not be stored or flowing
END DESCRIPTION:
XS GIS Cut Line= 5
     3209155.368    13909984.171     3210317.066    13909500.975
     3208852.658    13910109.191     3208701.399     13910173.92
     3207515.033    13910690.517
#Sta/Elev= 30
       0   44.39  422.04   48.02  563.12   45.76  613.44   48.63 1003.36   50.64
 1140.42   48.98 1811.28    49.6 1913.73   48.48 1953.26   45.77 2094.82   48.01
 2439.81   45.34  2479.2    43.5 2531.59   44.83 2795.31   42.26 2813.59   40.32
 2852.07   41.77 2880.72   36.35 2896.02   27.06 2898.28   22.97 2903.24   22.78
  2909.4   22.83 2912.05   28.92 2935.24   36.19 2951.38   37.73 2967.31   43.24
 2982.98   43.95 2988.05   41.85 3037.47   44.67 3292.12   50.56 4302.36   51.32
#Mann= 5 ,-1 , 0
       0     .11       0 2439.81     .99       0 2531.59     .11       0
 2852.07    .045       0 2967.31     .11       0
#Block Obstruct= 2 , 0
       0 1003.36   50.64               0
Bank Sta=2852.07,2967.31
Exp/Cntr=0.3,0.1

Type RM Length L Ch R = 1 ,22198.61,957.17,1018,972.1
BEGIN DESCRIPTION:
442v19
Manning's .99 in ROB is lateral drainage channel.
END DESCRIPTION:
XS GIS Cut Line= 4
     3209866.204    13908777.963     3209172.194    13908885.457
     3209052.474    13908960.007      3208362.03     13909127.66
#Sta/Elev= 30
       0   48.81  152.11   48.23  219.27   46.19  468.06   45.86   517.3    43.3
  614.42   43.44  687.27   39.59  707.41   37.33  713.16   34.27  727.12   31.95
  733.72   29.25  742.73   28.35  747.81   26.23  751.56   21.87  759.93   20.89
  768.78   23.27  785.28   34.78  807.94   36.87  829.91   43.76  869.56   42.67
  915.57   28.87  920.09   28.54  940.72   30.05   966.4   36.83  981.83   38.58
 1081.19   40.92 1206.27   37.72  1248.1   39.12  1300.9   45.69 1553.83   46.74
#Mann= 4 ,-1 , 0
       0     .11       0  707.41    .045       0  807.94     .11       0
  869.56     .99       0
Bank Sta=707.41,807.94
Exp/Cntr=0.3,0.1

Type RM Length L Ch R = 1 ,21180.61,1159.84,1294.7,1191.76
BEGIN DESCRIPTION:
442v18
END DESCRIPTION:
XS GIS Cut Line= 4
     3209560.562    13907601.976     3208836.493     13908017.64
     3208707.111    13908162.911     3208062.391    13908562.072
#Sta/Elev= 30
       0   46.07   62.89   47.82  210.72    45.2  450.84   44.45  576.41   40.03
  851.16   37.11  875.95   33.89  887.25   30.89  908.16   26.89  914.85   23.97
  919.26   19.12  921.76   18.89  931.25   19.16  935.05   25.74  939.21   28.53
  947.49   29.95  981.15   30.65 1011.54   35.55 1023.75   35.92 1033.14   34.31
 1056.19    36.5 1059.01   37.96 1124.62   41.29 1218.33      43 1285.68   42.53
 1331.92   45.93 1559.26   47.14 1594.37   44.86 1667.77   47.55 1787.71    46.9
#Mann= 3 ,-1 , 0
       0     .11       0  887.25    .045       0  947.49     .11       0
Bank Sta=887.25,947.49
Exp/Cntr=0.3,0.1

Type RM Length L Ch R = 1 ,19885.91,768.74,1004.7,821.18
BEGIN DESCRIPTION:
442v34
Additional xsec, need mannings, etc.
END DESCRIPTION:
XS GIS Cut Line= 5
     3209163.203    13906738.114     3208311.928    13907078.408
     3208093.278    13907231.086      3207653.05    13907453.135
     3207499.093    13907523.315
#Sta/Elev= 30
       0   44.44   63.43   46.65  350.18   45.72  461.19   43.89  509.15    43.8
  577.47   42.91  663.43   40.41  808.06   40.32  863.32   39.38  873.85   37.38
  957.87   30.77 1005.91   27.48 1016.74    20.1 1017.09   19.53 1027.11   19.38
  1037.9    19.9 1048.87   26.88  1063.5   28.67 1074.18   31.65 1085.21   32.23
 1121.03   32.41 1147.42   33.38  1198.1   37.45 1213.08   38.28 1294.98   41.37
 1433.75   43.55 1453.47   44.93 1534.75   45.54 1587.11   48.49 1845.71   49.84
#Mann= 3 ,-1 , 0
       0     .11       0  957.87    .045       0 1085.21     .11       0
Bank Sta=957.87,1085.21
Exp/Cntr=0.3,0.1