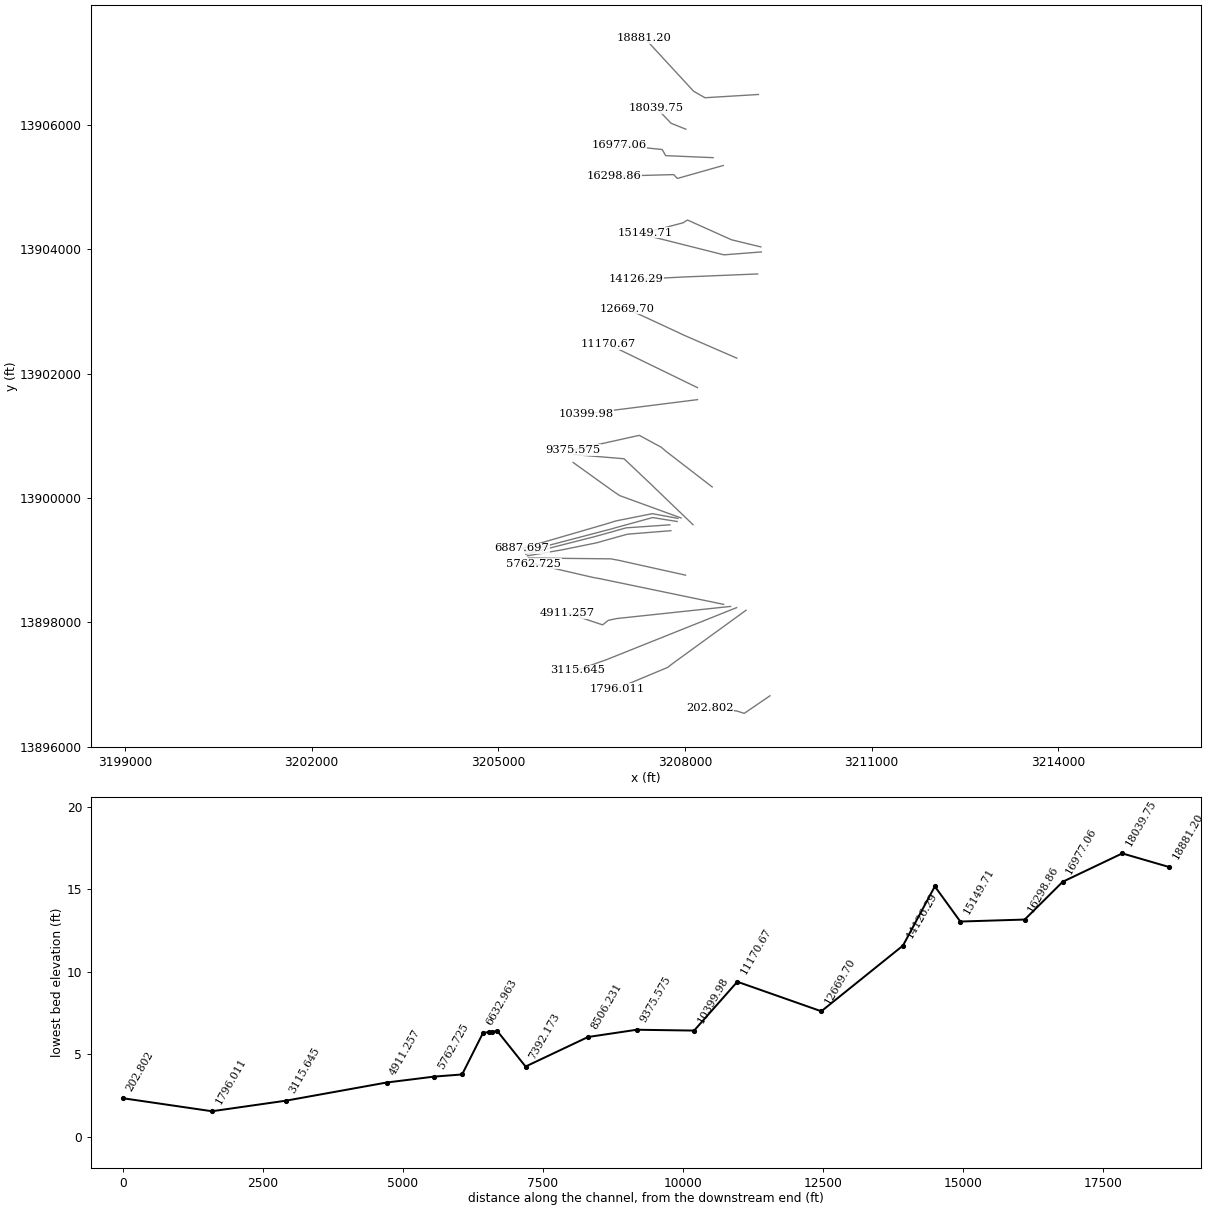
HEC-RAS study R102-00-00.prj: R102-00-00

--- R102-00-00.g03 (geometry) --- (continued)

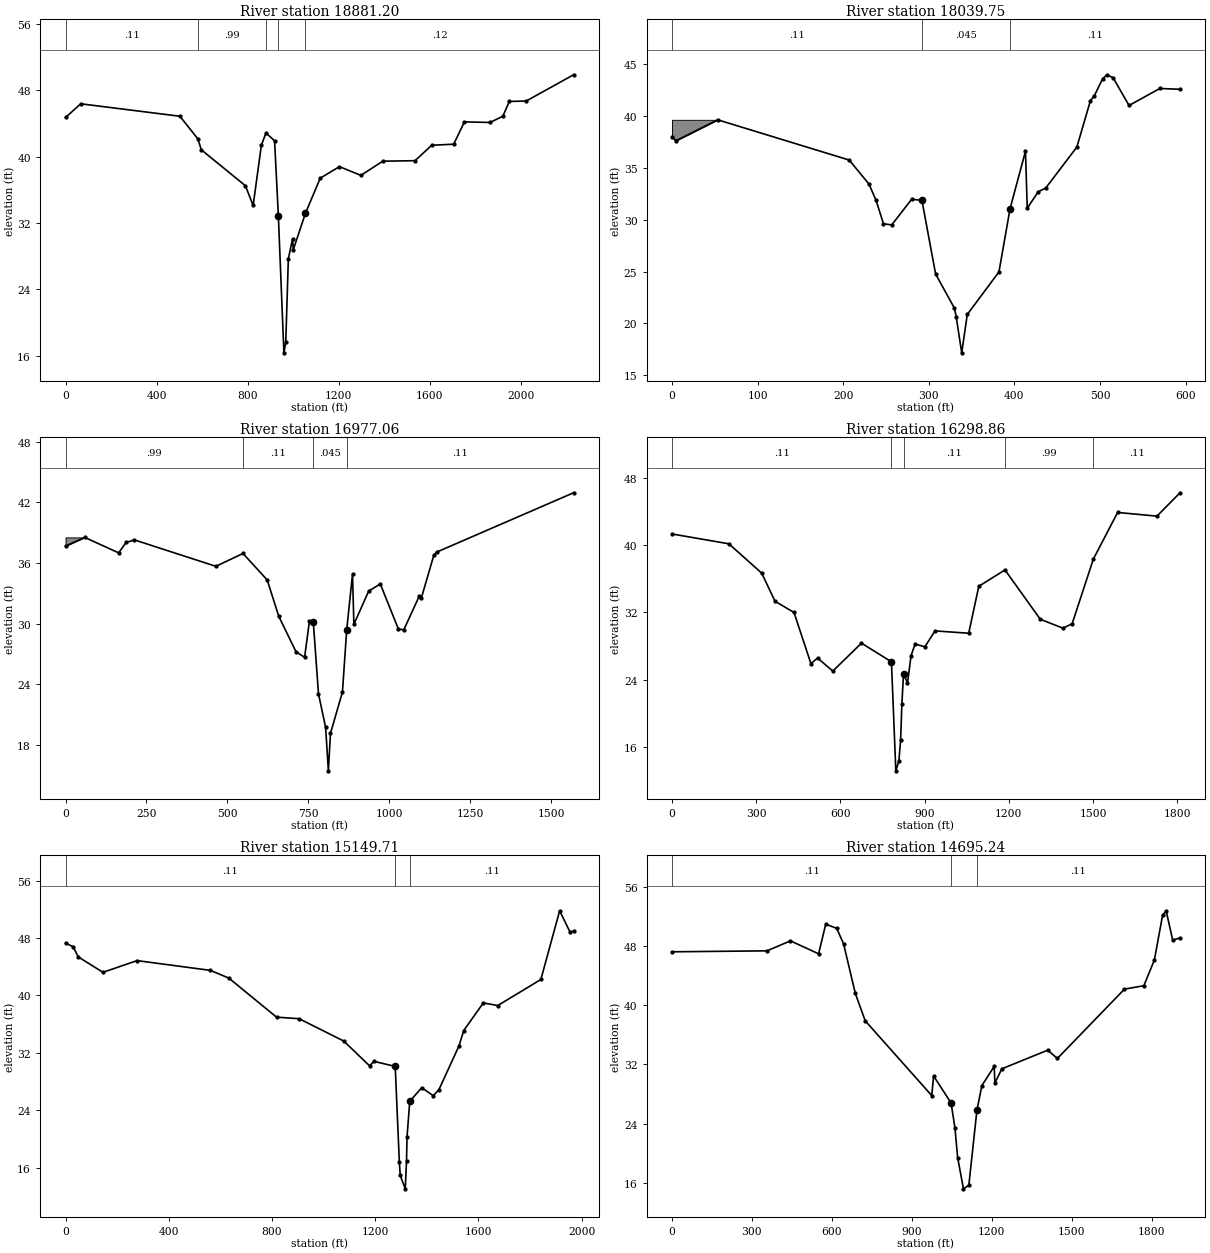
Type RM Length L Ch R = 1 ,18881.20,712.31,841.45,672.54
BEGIN DESCRIPTION:
442v33
Additional xsec
Manually removed low points near left channel station based on survey and LIDAR.
END DESCRIPTION:
XS GIS Cut Line= 5
      3209179.98    13906482.659     3208321.116    13906430.607
     3208138.932    13906534.712     3207414.537    13907319.835
     3207349.471    13907384.901
#Sta/Elev= 30
       0   44.72   67.03   46.37   502.1   44.87  581.51   42.13  596.06   40.83
  789.82   36.49  823.83   34.11  859.88   41.37  880.11   42.85  918.03   41.91
   934.6   32.81  958.88   16.34  967.01    17.6  978.39   27.68  996.76   30.07
 1000.19   28.79 1053.18   33.15 1118.57   37.41 1202.72   38.79 1296.91   37.74
    1393   39.45 1534.64   39.51 1607.67   41.37 1704.35    41.5 1751.41   44.19
 1863.95   44.12 1920.16   44.87 1948.46   46.65 2023.01   46.71 2230.54   49.87
#Mann= 5 ,-1 , 0
       0     .11       0  581.51     .99       0  880.11     .11       0
   934.6    .045       0 1053.18     .12       0
Bank Sta=934.6,1053.18
Exp/Cntr=0.3,0.1

Type RM Length L Ch R = 1 ,18039.75,513.94,1062.69,659.03
BEGIN DESCRIPTION:
442v17
New xsec, upstream of 442v17 survey
Need mannings, etc.
END DESCRIPTION:
XS GIS Cut Line= 3
      3208014.04    13905924.685      3207775.94    13906020.693
       3207543.6    13906264.554
#Sta/Elev= 30
       0   38.01    4.41    37.6   53.39   39.63  207.09   35.75  230.15   33.44
  238.47   31.86  247.07   29.61  256.73    29.5  280.01   31.97  292.01   31.87
  308.01   24.77  330.01   21.47  332.01   20.67  338.51   17.17  345.01   20.87
  382.01   24.97  395.01   31.07  413.01    36.6  415.06   31.11  427.89   32.69
  436.71   33.06  473.01      37  488.94   41.49  493.13    41.9   503.2   43.59
  508.11   43.97  515.34   43.69     534   41.01  569.91   42.65  593.55   42.57
#Mann= 3 ,-1 , 0
       0     .11       0  292.01    .045       0  395.01     .11       0
#Block Obstruct= 1 ,-1
       0   53.39   39.63
Bank Sta=292.01,395.01
Exp/Cntr=0.3,0.1

Type RM Length L Ch R = 1 ,16977.06,382.47,678.2,535.6
BEGIN DESCRIPTION:
442v17
New xsec, downstream of 442v17 survey
Need mannings, etc.
Manning's .99 includes side ditch or gully, located only in this xsec.
END DESCRIPTION:
XS GIS Cut Line= 4
     3208451.837    13905467.686     3207689.533    13905500.329
     3207633.848    13905598.257     3206944.509    13905671.223
#Sta/Elev= 30
       0   37.67   59.23   38.53  164.12      37  187.25   38.03  212.87   38.28
  464.39   35.67  548.09   36.94  622.92   34.32  658.26   30.75  711.95   27.21
  738.37   26.68  753.25   30.25  765.25   30.15  781.25   23.05  803.25   19.75
  811.75   15.45  818.25   19.15  855.25   23.25  868.25   29.35  886.25   34.88
  890.52   29.94  936.38   33.23  972.17   33.92  1027.9   29.47 1044.56   29.39
 1092.84   32.75 1098.67   32.51 1137.34   36.76 1146.53   37.08 1568.85   42.94
#Mann= 4 ,-1 , 0
       0     .99       0  548.09     .11       0  765.25    .045       0
  868.25     .11       0
#Block Obstruct= 1 ,-1
       0   59.23   38.53
Bank Sta=765.25,868.25
Exp/Cntr=0.3,0.1

Type RM Length L Ch R = 1 ,16298.86,934.3,1149.15,871.59
BEGIN DESCRIPTION:
442v16
Manning's .99 in ROB is a perpendicular gully unique to xsec.
END DESCRIPTION:
XS GIS Cut Line= 4
     3208614.139    13905341.807     3207877.498    13905133.569
     3207819.173    13905195.464     3206860.447    13905170.035
#Sta/Elev= 30
       0   41.34   202.7   40.17  319.58   36.68  367.22   33.33  434.73      32
  494.93   25.91  518.54   26.58  572.87   25.03  674.94   28.35  781.75   26.13
  797.37   13.16  808.18   14.32  814.41   16.81     819   21.17  824.89   24.74
  838.83   23.58  851.68   26.87  865.91   28.23  901.02   27.92  936.74   29.81
 1056.93   29.53 1092.93   35.12 1186.17   37.06 1312.02   31.19 1393.02   30.13
 1425.49   30.67 1501.12   38.37 1587.44    43.9 1727.53   43.46 1809.62   46.24
#Mann= 5 ,-1 , 0
       0     .11       0  781.75    .045       0  824.89     .11       0
 1186.17     .99       0 1501.12     .11       0
Bank Sta=781.75,824.89
Exp/Cntr=0.3,0.1

Type RM Length L Ch R = 1 ,15149.71,431.02,454.47,407.15
BEGIN DESCRIPTION:
442v15
END DESCRIPTION:
XS GIS Cut Line= 6
      3209219.55    13904033.765     3208746.711    13904148.661
     3208040.088    13904465.905     3207970.036    13904421.629
      3207553.13    13904311.202     3207365.918    13904264.399
#Sta/Elev= 30
       0   47.31   30.09   46.78   49.22   45.38  145.12   43.23  277.16   44.86
   561.6    43.5  632.92   42.42  817.54   36.98  905.22   36.76 1077.86   33.65
 1177.95   30.19 1195.34   30.81 1277.42   30.11 1293.29   16.84 1296.87    14.9
 1316.27   13.04 1321.22   16.96 1323.06   20.22 1333.77   25.25 1380.06   27.14
 1424.76   26.03  1446.9   26.89 1524.25   32.95 1542.83   35.11 1618.65   38.96
 1674.87    38.6  1841.7   42.23 1914.45   51.81 1954.12   48.88  1968.3   48.94
#Mann= 3 , 0 , 0
       0     .11       0 1277.42    .045       0 1333.77     .11       0
Bank Sta=1277.42,1333.77
Exp/Cntr=0.3,0.1

Type RM Length L Ch R = 1 ,14695.24,444.17,568.96,505.86
BEGIN DESCRIPTION:
442v14
END DESCRIPTION:
XS GIS Cut Line= 3
     3209226.332     13903953.16     3208624.915    13903906.357
     3207361.238    13904224.617
#Sta/Elev= 30
       0   47.24  356.43   47.37  444.64   48.72  550.12   46.97  576.99   50.98
  618.04   50.42  644.07    48.3  687.84   41.63  725.02   37.91  974.74   27.79
  981.75   30.44 1047.37   26.78 1061.85    23.4 1071.96    19.4 1093.81   15.17
 1113.92   15.65 1144.34   25.82 1162.93   29.14    1209   31.73 1211.76    29.5
  1237.8   31.41 1409.87   33.93 1446.21   32.81 1697.97   42.19 1770.63   42.65
 1810.27   46.14 1840.89   52.17  1854.3   52.79 1878.91   48.82 1906.37   49.11
#Mann= 3 ,-1 , 0
       0     .11       0 1047.37    .045       0 1144.34     .11       0
Bank Sta=1047.37,1144.34
Exp/Cntr=0.3,0.1

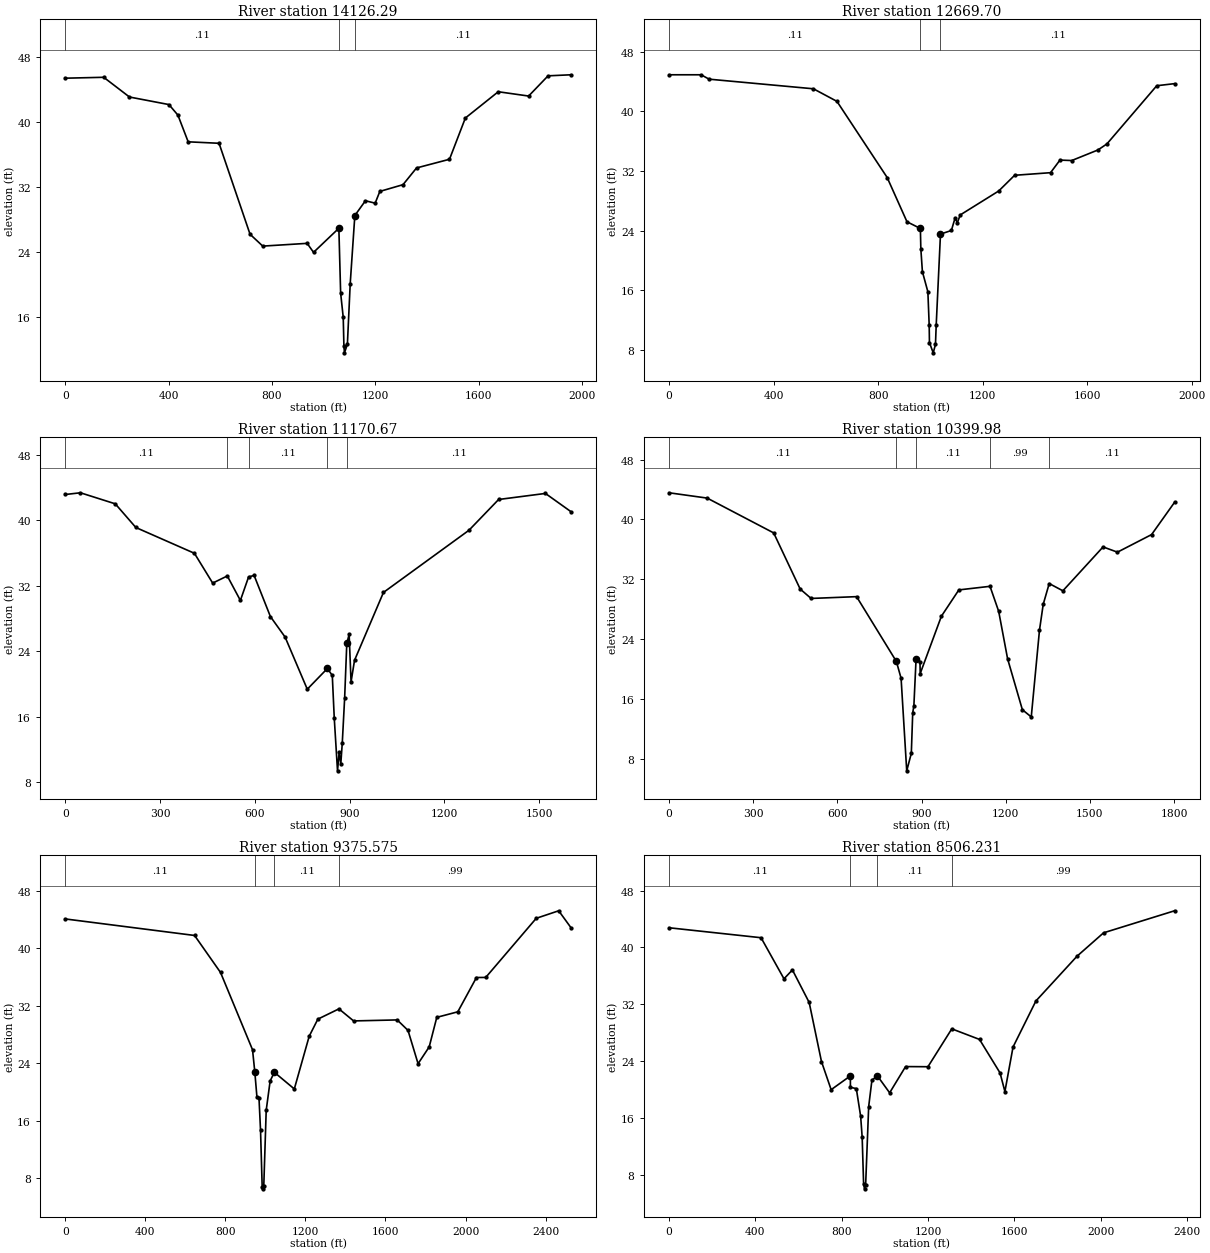
Type RM Length L Ch R = 1 ,14126.29,1261.03,1456.59,907.3
BEGIN DESCRIPTION:
442v13
END DESCRIPTION:
XS GIS Cut Line= 4
      3209167.34    13903599.464     3208141.744    13903557.059
     3208026.161    13903553.044     3207212.023    13903511.674
#Sta/Elev= 30
       0   45.42  148.41   45.53  248.15    43.1   400.9   42.17   435.7   40.87
  475.44   37.58  594.98    37.4  715.08   26.19  764.26   24.73  936.13   25.07
  960.87   23.96 1058.91   26.93 1065.79   18.94 1075.84   15.95 1078.43   12.46
 1080.56   11.58 1091.94   12.64 1102.87   20.11 1120.77    28.5 1161.77   30.32
 1199.44   30.02 1217.57   31.47 1307.28    32.3 1359.67   34.36 1487.29   35.43
 1548.67   40.51  1676.1   43.75 1793.65   43.22 1868.98   45.71 1957.31   45.84
#Mann= 3 , 0 , 0
       0     .11       0 1058.91    .045       0 1120.77     .11       0
Bank Sta=1058.91,1120.77
Exp/Cntr=0.3,0.1

Type RM Length L Ch R = 1 ,12669.70,797.07,1499.03,751.64
BEGIN DESCRIPTION:
442v12
END DESCRIPTION:
XS GIS Cut Line= 4
     3208832.143    13902246.704     3207974.847    13902619.171
     3207863.744    13902672.362     3207068.367    13903040.802
#Sta/Elev= 30
       0   44.92  122.77   44.92  153.19   44.33  552.45   43.04  642.49   41.35
  834.68   31.13  910.49   25.19  961.72   24.29   963.5   21.55  969.49   18.49
  990.44   15.79  995.45   11.32  996.44    8.97 1010.91     7.6 1019.52    8.73
 1022.28   11.31 1038.67   23.54 1080.37   24.02 1094.52    25.7 1102.94   25.05
 1114.38   26.11  1261.4   29.32 1322.36   31.43  1459.9   31.78  1495.9   33.47
    1541   33.41 1641.33   34.83 1675.56   35.64 1866.29   43.45 1934.46   43.73
#Mann= 3 ,-1 , 0
       0     .11       0  961.72    .045       0 1038.67     .11       0
Bank Sta=961.72,1038.67
Exp/Cntr=0.3,0.1

Type RM Length L Ch R = 1 ,11170.67,605.58,770.69,748.53
BEGIN DESCRIPTION:
442v11
END DESCRIPTION:
XS GIS Cut Line= 2
     3208200.984    13901772.589     3206762.154    13902472.769
#Sta/Elev= 30
       0   43.14   47.63   43.35  157.98      42  223.04   39.11  408.47   35.96
  466.26   32.32  512.58   33.19  553.96    30.2  579.92   33.07  597.38   33.26
  649.03   28.23  695.47   25.73   765.7   19.36  829.35   21.89  844.88   21.04
  851.17   15.79  861.45    9.39  866.67   11.65  871.83   10.25  876.48   12.78
  884.01    18.3  890.78   24.95  898.23   26.06  904.28   20.25  915.28   22.89
 1006.86   31.18 1277.48   38.77 1371.37   42.53 1519.52   43.27 1600.15   41.05
#Mann= 5 ,-1 , 0
       0     .11       0  512.58     .99       0  579.92     .11       0
  829.35    .045       0  890.78     .11       0
Bank Sta=829.35,890.78
Exp/Cntr=0.3,0.1

Type RM Length L Ch R = 1 ,10399.98,843.13,1024.4,637.29
BEGIN DESCRIPTION:
442v10
Manning's .99 in ROB is perpendicular stream crossed by xsec line.
END DESCRIPTION:
XS GIS Cut Line= 2
     3208200.984    13901580.232     3206413.346    13901354.534
#Sta/Elev= 30
       0   43.56  135.87   42.85  372.93    38.2  467.26   30.71  506.29   29.45
  668.38   29.69  810.21   21.04  827.04   18.79  847.13    6.43  863.51    8.77
   868.5   14.18   872.6    15.1  880.39   21.31  894.38   21.03  895.16   19.42
  970.76   27.08 1032.94   30.59 1143.99   31.07 1174.91   27.73 1206.69   21.39
 1259.34   14.59 1291.02   13.63 1320.33   25.21 1333.62   28.66 1355.02   31.44
 1403.72   30.47 1547.01   36.33 1598.22   35.63 1719.97   37.98 1801.83   42.29
#Mann= 5 ,-1 , 0
       0     .11       0  810.21    .045       0  880.39     .11       0
 1143.99     .99       0 1355.02     .11       0
Bank Sta=810.21,880.39
Exp/Cntr=0.3,0.1

Type RM Length L Ch R = 1 ,9375.575,676.42,869.34,564.26
BEGIN DESCRIPTION:
442v9
END DESCRIPTION:
XS GIS Cut Line= 5
      3208437.07    13900177.363     3207693.575    13900751.123
     3207619.741    13900814.844     3207265.717    13901006.215
     3206203.836    13900771.348
#Sta/Elev= 30
       0   44.09  645.69   41.79  775.53   36.63  935.46   25.86  946.97   22.72
  957.55   19.23  967.71   19.14  975.43   14.64  983.73    6.68  987.71    6.48
  991.62    6.87 1003.79   17.43 1023.49   21.52 1044.48   22.72 1144.25    20.4
 1218.69   27.75 1261.96   30.13 1367.33   31.56 1440.57   29.88 1658.61   30.02
 1712.54   28.56 1762.86   23.92 1818.43   26.26  1856.4   30.38 1961.41   31.15
 2054.63   35.93 2100.95   35.94 2353.44   44.18 2465.68   45.23 2526.65   42.89
#Mann= 4 ,-1 , 0
       0     .11       0  946.97    .045       0 1044.48     .11       0
 1367.33     .99       0
Bank Sta=946.97,1044.48
Exp/Cntr=0.3,0.1

Type RM Length L Ch R = 1 ,8506.231,352.28,1114.06,538.66
BEGIN DESCRIPTION:
442v8
Forced ineffective in ROB is tributary, blocked from upstream model flow by terrain.
END DESCRIPTION:
XS GIS Cut Line= 5
     3208128.819    13899571.136     3207506.959    13900168.534
     3207448.026    13900226.115     3207020.331    13900630.551
     3206214.588    13900697.374
#Sta/Elev= 30
       0   42.77  426.16   41.37  532.45   35.59  571.49   36.84  649.14   32.26
  706.07   23.95   750.9   19.99  839.94   21.93  840.15   20.33  867.52   20.14
  887.56   16.25  894.61   13.31  901.31    6.69   905.5    6.04  910.57    6.51
  924.76   17.62  939.84   21.33  965.23   21.93 1021.89   19.55 1095.69   23.24
 1199.41   23.22 1309.81   28.55 1438.24   27.06 1533.35   22.35 1555.88   19.73
 1593.52   25.99  1699.5   32.47 1890.02   38.77 2012.99   42.06 2341.86   45.16
#Mann= 4 ,-1 , 0
       0     .11       0  839.94    .045       0  965.23     .11       0
 1309.81     .99       0
Bank Sta=839.94,965.23
Exp/Cntr=0.3,0.1

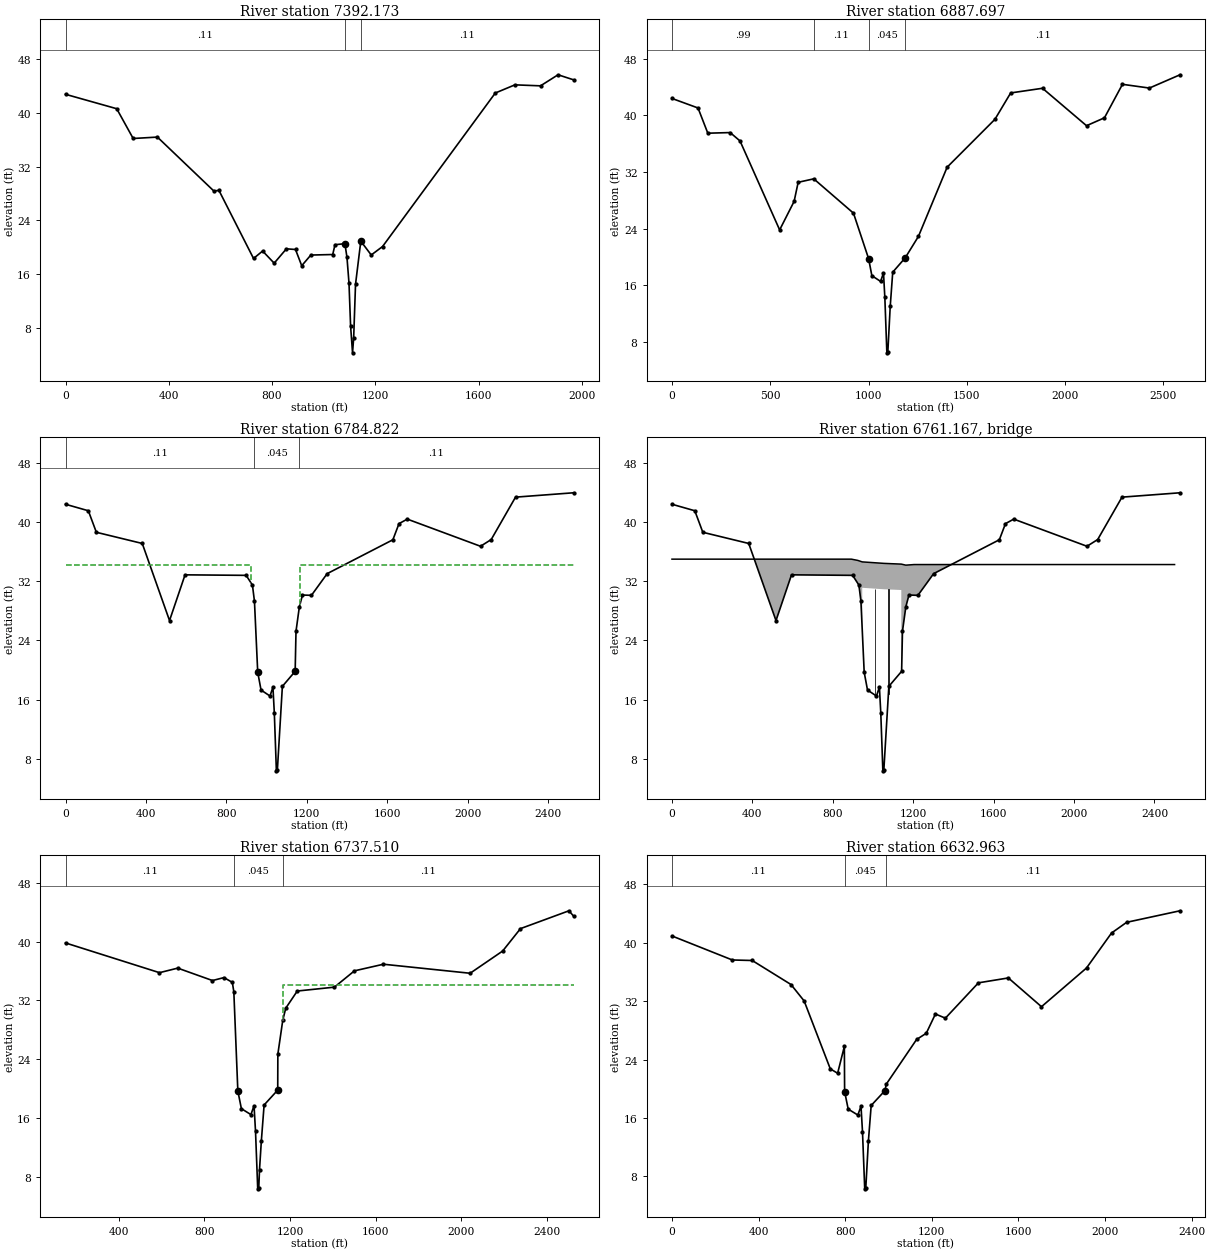
Type RM Length L Ch R = 1 ,7392.173,492.66,504.48,541
BEGIN DESCRIPTION:
442v7
END DESCRIPTION:
XS GIS Cut Line= 4
     3207937.402    13899678.688     3206951.505    13900037.859
     3206843.886    13900110.573     3206202.868    13900570.607
#Sta/Elev= 30
       0    42.8  198.37   40.65  262.14   36.21  356.01   36.42   574.9   28.37
   594.3   28.48  728.43   18.32  763.62   19.43  808.36   17.62  855.75   19.76
  891.02   19.66  915.09   17.24  950.45   18.83 1035.18   18.91 1044.02   20.37
 1082.38   20.53 1090.37    18.5 1098.24   14.64 1104.44    8.26 1111.97    4.25
 1116.39    6.51 1123.55   14.47 1144.02    20.9  1184.4   18.84 1228.23    20.1
 1664.98   42.99 1741.08   44.21 1840.19   44.06 1908.13   45.71 1968.17   44.96
#Mann= 3 ,-1 , 0
       0     .11       0 1082.38    .045       0 1144.02     .11       0
Bank Sta=1082.38,1144.02
Exp/Cntr=0.3,0.1

Type RM Length L Ch R = 1 ,6887.697,112.97,102.88,101.88
BEGIN DESCRIPTION:
Xsec 4/4 of Diamondhead Blvd., 442s1u
END DESCRIPTION:
XS GIS Cut Line= 5
     3207886.373    13899672.569     3207475.312    13899747.992
     3206887.986    13899631.086     3206737.878    13899584.003
     3205383.805    13899190.473
#Sta/Elev= 30
       0   42.41  132.52   41.06  182.31   37.49  295.98   37.58  346.18   36.39
  547.68    23.8  621.29   27.84  641.86   30.54   721.2   31.03  923.24   26.17
 1000.23   19.73 1016.77   17.32 1061.34   16.51 1075.91   17.72 1082.77   14.25
 1093.09     6.4 1097.85    6.45 1110.09   12.96 1122.91   17.82 1186.48   19.85
 1253.42   22.87 1399.66   32.68 1642.87   39.46 1722.91   43.19 1884.81   43.85
 2108.65   38.55 2199.85   39.67 2291.41   44.41 2428.46   43.88 2584.19   45.76
#Mann= 4 ,-1 , 0
       0     .99       0   721.2     .11       0 1000.23    .045       0
 1186.48     .11       0
Bank Sta=1000.23,1186.48
Exp/Cntr=0.5,0.3

Type RM Length L Ch R = 1 ,6784.822,47.31,47.31,48.31
BEGIN DESCRIPTION:
Xsec 3/4 of Diamondhead Blvd., copy of 442s1u
Elevations adjusted based on slope between 442v7 and 442v6
END DESCRIPTION:
XS GIS Cut Line= 6
     3207873.802    13899622.287     3207479.194    13899685.333
     3206878.902    13899520.617     3206850.205    13899511.897
     3206818.061    13899502.774     3205423.576    13899137.445
#Sta/Elev= 30
       0   42.39  113.57   41.51  153.43    38.6  381.75   37.09   517.4   26.67
   594.6   32.85  898.59   32.78  929.84   31.46  939.87   29.28  956.08   19.69
  972.62   17.28 1017.19   16.47 1031.76   17.68 1038.62   14.21 1048.94    6.36
  1053.7    6.41 1078.76   17.78 1142.33   19.81 1146.49   25.22 1163.23   28.53
 1178.73   30.12 1223.39   30.08 1301.51   33.01 1628.41   37.59 1658.85   39.77
 1700.07   40.38 2064.32   36.71 2117.49   37.62 2238.44   43.35 2527.04   43.94
#Mann= 3 ,-1 , 0
       0     .11       0  939.87    .045       0 1163.23     .11       0
#XS Ineff= 2 , 0
       0  921.66   34.16 1165.37       0   34.16
Permanent Ineff=
       F       F
Bank Sta=956.08,1142.33
Exp/Cntr=0.5,0.3

Type RM Length L Ch R = 3 ,6761.167,,,
BEGIN DESCRIPTION:
442s1, Diamondhead Blvd.
Downstream section (2/4) stationing shifted 151.33' to the right to line up the u/s and d/s faces of the structure for floodways
END DESCRIPTION:
Bridge Culvert--1,0,-1,-1, 0
Deck Dist Width WeirC Skew NumUp NumDn MinLoCord MaxHiCord MaxSubmerge Is_Ogee
6.5,34.4,2.6,0, 11, 11, , , 0.95, 0, 0,0,,
       0  892.49   924.2   946.4   946.4 1053.87 1140.63 1140.63 1163.04 1204.77
    2500
   34.97   34.97    34.8    34.6    34.6    34.4    34.3    34.3   34.16   34.24
   34.24
       0       0       0       0    31.1    30.9    30.8       0       0       0
       0
  151.33  892.82  924.53  946.73  946.73  1054.2 1140.96 1140.96 1163.37  1205.1
 2651.33
   34.97   34.97    34.8    34.6    34.6    34.4    34.3    34.3   34.16   34.24
   34.24
       0       0       0       0    31.1    30.9    30.8       0       0       0
       0
Pier Skew, UpSta & Num, DnSta & Num=  ,1010.8, 4 ,1011.13, 4 , 3 , 3 , 0 ,0,
     1.3     1.3       2       2
       5   28.45   28.45   31.47
     1.3     1.3       2       2
       5   28.45   28.45   31.47
Pier Skew, UpSta & Num, DnSta & Num=  ,1076.39, 4 ,1076.72, 4 , 3 , 3 , 0 ,0,
     1.3     1.3       2       2
       5   28.35   28.35   31.47
     1.3     1.3       2       2
       5   28.35   28.35   31.47
BR Coef= 1 , 1 , 0 ,, 0 ,,,0.8,-1,2,0,
WSPro=,,,, 1 ,,,, 0 ,,,, 0 ,,,,-1 ,-1 ,-1 , 0 , 0 , 0 , 0 , 0
BC Design=,, 0 ,, 0 ,,,,,,
BC HTab HWMax=43.94

Type RM Length L Ch R = 1 ,6737.510,104.55,104.55,104.98
BEGIN DESCRIPTION:
xsec 2/4 of Diamondhead Blvd., copy of 442s1u
Elevations adjusted based on slope between 442v7 and 442v6
END DESCRIPTION:
XS GIS Cut Line= 6
     3207757.524    13899568.862     3207056.355    13899520.313
     3206894.612    13899475.931     3206833.771    13899458.089
     3206554.112    13899380.323     3205441.252    13899097.673
#Sta/Elev= 30
  151.33   39.83  590.16   35.78  675.46    36.4  837.62   34.71  891.33   35.11
  930.38   34.46  937.38   33.17  956.08   19.67  972.62   17.26 1017.19   16.45
 1031.76   17.66 1038.62   14.19 1048.94    6.34  1053.7    6.39 1057.31    8.97
 1065.94    12.9 1078.76   17.76 1142.33   19.79 1142.93   24.68 1165.89    29.3
 1179.97   30.95 1233.66   33.28 1407.15   33.81 1500.55   36.03 1635.97   36.93
 2040.82    35.7 2192.78   38.73 2275.98   41.78 2502.41   44.21 2523.77   43.49
#Mann= 3 ,-1 , 0
  151.33     .11       0  937.38    .045       0 1165.89     .11       0
#XS Ineff= 2 , 0
  151.33  921.99   34.16  1165.7  151.33   34.16
Permanent Ineff=
       F       F
Bank Sta=956.08,1142.33
Exp/Cntr=0.5,0.3

Type RM Length L Ch R = 1 ,6632.963,405.46,373.22,327.01
BEGIN DESCRIPTION:
xsec 1/4 of Diamondhead Blvd., copy of 442s1u
Elevations adjusted based on slope between 442v7 and 442v6
END DESCRIPTION:
XS GIS Cut Line= 6
     3207773.237    13899474.583     3207077.572    13899418.602
     3206915.829    13899374.221     3206575.329    13899278.612
     3206022.786    13899166.604     3205467.767    13899071.159
#Sta/Elev= 30
       0   40.93  278.68   37.64  370.59   37.57   549.6   34.28  610.39   32.03
  731.12   22.73  765.01   22.12  796.12    25.8  797.31   19.62  813.85   17.21
  858.42    16.4  872.99   17.61  879.85   14.14  890.17    6.29  894.93    6.34
  907.17   12.85  919.99   17.71  983.56   19.74  989.68   20.63 1129.74   26.75
 1174.38    27.6 1216.71   30.24 1262.63   29.67  1415.3   34.51 1553.43   35.18
 1706.48   31.24 1914.39   36.54 2029.95   41.33 2099.76    42.8 2346.26   44.38
#Mann= 3 ,-1 , 0
       0     .11       0  797.31    .045       0  989.68     .11       0
Bank Sta=797.31,983.56
Exp/Cntr=0.3,0.1

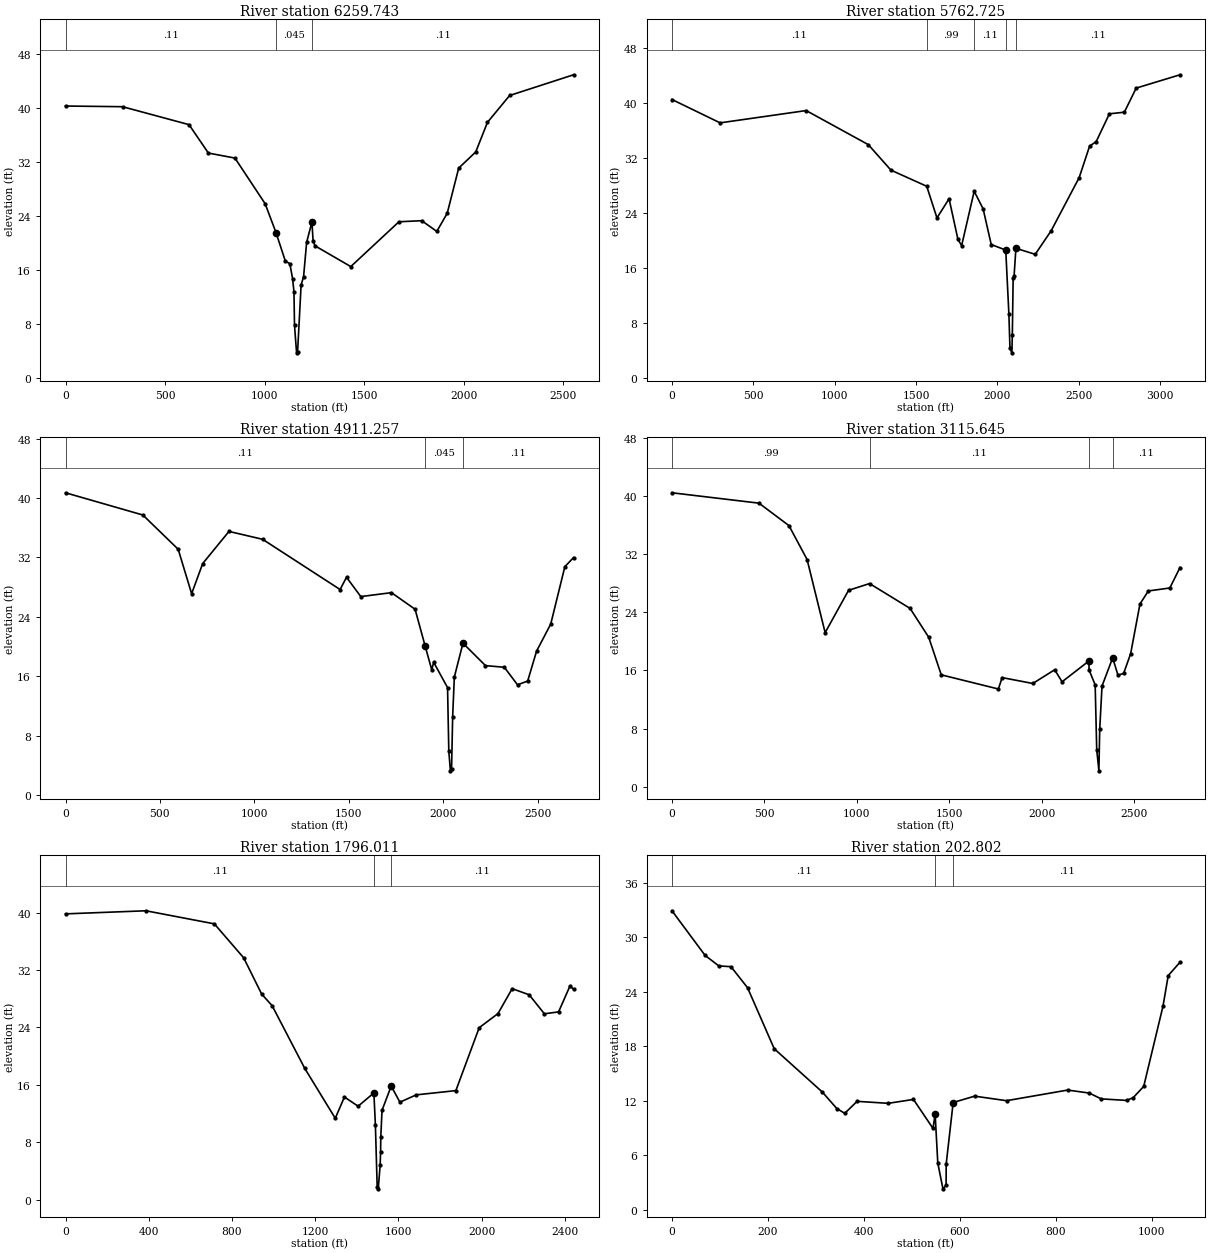
Type RM Length L Ch R = 1 ,6259.743,431.74,497.02,450.42
BEGIN DESCRIPTION:
442v6
END DESCRIPTION:
XS GIS Cut Line= 4
     3208008.621     13898760.31     3206925.082    13899000.747
     3206808.114    13899022.198     3205485.443    13899035.806
#Sta/Elev= 30
       0   40.34  286.46   40.24  620.34   37.58  717.63   33.37  850.96   32.63
 1002.73   25.86 1057.14   21.59 1104.16   17.36  1126.7   16.98 1140.55   14.75
 1147.41    12.8 1150.11    7.83 1160.57    3.77 1165.46    3.84 1183.29   13.83
 1195.67   15.05 1210.99   20.14 1237.62   23.15 1243.37   20.41 1252.78   19.63
  1432.8   16.55 1674.55   23.19 1789.09   23.35  1864.8   21.76 1917.22   24.46
 1974.71   31.14 2060.46   33.54  2119.1   37.92 2230.57    41.9 2551.56   44.97
#Mann= 3 ,-1 , 0
       0     .11       0 1057.14    .045       0 1237.62     .11       0
Bank Sta=1057.14,1237.62
Exp/Cntr=0.3,0.1

Type RM Length L Ch R = 1 ,5762.725,650.19,851.47,727.42
BEGIN DESCRIPTION:
442v5
END DESCRIPTION:
XS GIS Cut Line= 4
     3208620.396    13898290.905     3206633.186    13898703.618
     3206518.701    13898724.251     3205568.298    13898943.926
#Sta/Elev= 30
       0   40.52   295.7   37.12  824.51   38.91 1206.29   33.95 1345.16   30.24
 1565.23   27.89 1628.12   23.28 1702.47   26.07 1756.94   20.16 1779.71   19.25
 1856.76   27.16 1911.66   24.61 1961.44   19.41 2050.73    18.6 2070.05    9.27
 2076.58    4.32 2088.18    3.64 2091.15    6.22 2096.18   14.48 2102.03   14.87
 2113.18   18.86 2231.75   17.98 2329.64   21.41 2501.72   29.14 2565.88   33.73
 2606.59    34.4 2687.57   38.44 2779.33   38.67 2852.04   42.18  3121.4   44.12
#Mann= 5 ,-1 , 0
       0     .11       0 1565.23     .99       0 1856.76     .11       0
 2050.73    .045       0 2113.18     .11       0
Bank Sta=2050.73,2113.18
Exp/Cntr=0.3,0.1

Type RM Length L Ch R = 1 ,4911.257,1567.45,1795.61,1198.47
BEGIN DESCRIPTION:
442v4
END DESCRIPTION:
XS GIS Cut Line= 5
     3208733.453    13898258.051     3206908.381    13898063.613
     3206767.083    13898033.956     3206676.617    13897961.508
     3206112.427    13898150.191
#Sta/Elev= 30
       0    40.7  409.51   37.71  596.67    33.1  667.95   27.12  726.63   31.18
  865.82    35.5 1043.76   34.44 1454.25   27.68 1488.17   29.33 1563.89   26.73
 1726.05   27.26 1851.25   25.03 1904.28   20.11 1939.53   16.88 1949.81   17.89
 2023.32   14.48 2029.97    5.91 2038.44    3.28 2044.51    3.47 2050.36   10.59
 2059.23    15.9  2104.9   20.46 2224.16   17.44 2323.96   17.22  2393.8   14.86
 2447.52   15.36 2494.93    19.4 2569.74   23.03 2644.59   30.76 2690.58   31.98
#Mann= 3 ,-1 , 0
       0     .11       0 1904.28    .045       0  2104.9     .11       0
Bank Sta=1904.28,2104.9
Exp/Cntr=0.3,0.1

Type RM Length L Ch R = 1 ,3115.645,627.06,1319.63,1248.32
BEGIN DESCRIPTION:
442v3
END DESCRIPTION:
XS GIS Cut Line= 4
     3208829.746    13898238.568      3206728.33    13897398.111
     3206621.569    13897361.439     3206273.568    13897234.231
#Sta/Elev= 30
       0   40.47  470.52   39.04  632.38   35.95  730.53   31.28  828.04   21.21
  954.78   27.04 1068.26   27.97 1287.27   24.55 1388.17   20.57 1455.78    15.4
 1764.65   13.45 1784.92   15.02 1950.77   14.21  2069.1    16.1    2109   14.44
 2254.36   17.31 2254.72   16.09 2287.97   14.02 2296.32     5.1 2308.15    2.18
 2312.51    7.88 2325.03   13.86 2382.61   17.74 2411.14   15.36 2441.76   15.59
 2479.69   18.31 2530.22   25.16  2575.3   26.95 2691.56   27.36 2746.66   30.18
#Mann= 4 ,-1 , 0
       0     .99       0 1068.26     .11       0 2254.36    .045       0
 2382.61     .11       0
Bank Sta=2254.36,2382.61
Exp/Cntr=0.3,0.1

Type RM Length L Ch R = 1 ,1796.011,1539.46,1593.21,1163.17
BEGIN DESCRIPTION:
442v2
END DESCRIPTION:
XS GIS Cut Line= 4
     3208981.524    13898196.698     3207806.132    13897343.673
     3207722.034    13897278.192     3206906.824    13896937.392
#Sta/Elev= 30
       0   39.81  386.73   40.24  715.57   38.42  856.66   33.69  943.18   28.64
  993.42   27.03 1149.91   18.32 1296.86   11.36 1340.93   14.32 1406.75   13.04
 1482.58   14.89 1489.82   10.41 1498.52    1.73 1503.47    1.54 1512.63     4.8
 1514.84    6.72  1515.7    8.72 1521.71   12.47 1565.84   15.84 1607.76    13.6
 1686.15   14.62 1876.68   15.21 1988.91   23.97 2079.18   25.93  2147.3    29.4
 2229.08   28.55 2302.26    25.9 2370.59   26.17 2425.08   29.76 2442.47   29.33
#Mann= 3 ,-1 , 0
       0     .11       0 1482.58    .045       0 1565.84     .11       0
Bank Sta=1482.58,1565.84
Exp/Cntr=0.3,0.1

Type RM Length L Ch R = 1 ,202.802 ,427.72,202.8,202.8
BEGIN DESCRIPTION:
442v1 & 441v14 - do not enter 441v14.  common section floodplain block criteria applied.
New xsec upstream of 442v1
END DESCRIPTION:
XS GIS Cut Line= 4
     3209365.083    13896821.891     3208951.848    13896539.479
     3208831.408    13896577.895     3208402.598    13896626.694
#Sta/Elev= 30
       0   32.93   69.01   28.02   97.68   26.86  122.91   26.78  157.49   24.46
  213.02   17.75  313.31   12.98  343.58   11.16  359.99   10.64   385.7   11.96
  450.46   11.74  503.13   12.17  543.85    8.98  548.31   10.54  553.87    5.16
  564.57    2.33  571.17    2.74  571.34    5.06  585.88   11.83   630.5   12.53
  697.03   12.03  824.54    13.2  869.46   12.87  894.32   12.23  947.53   12.06
  961.28   12.38  982.87    13.6 1023.01   22.42 1033.97    25.8 1058.52   27.27
#Mann= 3 ,-1 , 0
       0     .11       0  548.31    .045       0  585.88     .11       0
Bank Sta=548.31,585.88
Exp/Cntr=0.3,0.1

Chan Stop Cuts=-1
Use User Specified Reach Order=0
User Specified Reach Order=R102-00-00      ,R102-00-00_0002